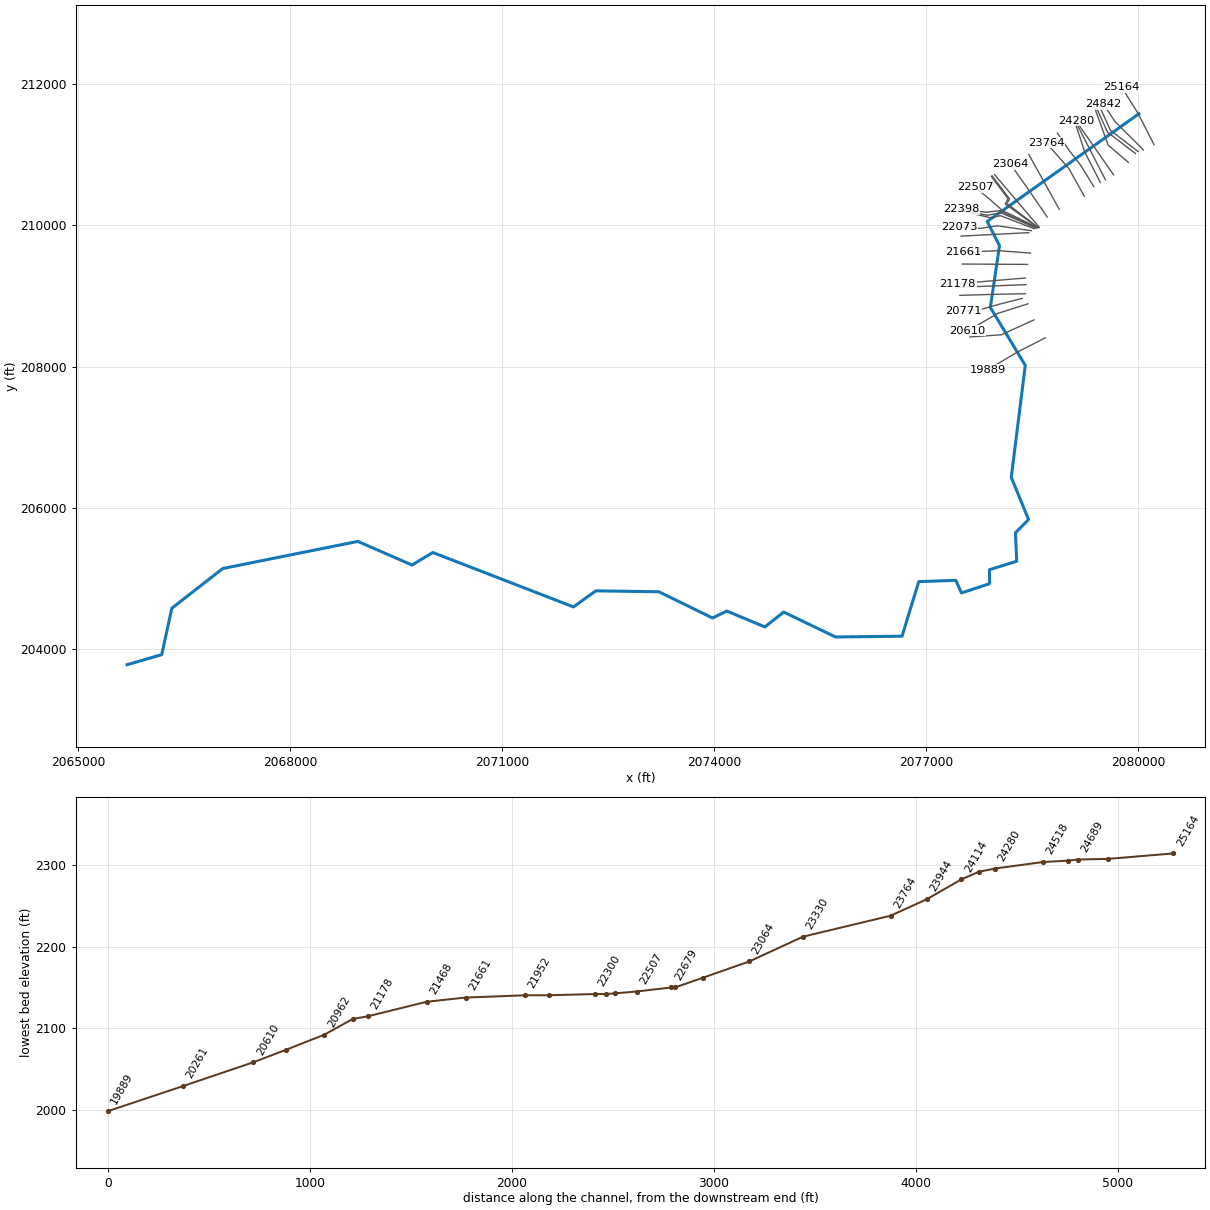
--- LAURELCK1.prj (project) ---

Proj Title=LAURELCK1
Current Plan=p01
Default Exp/Contr=0,0
English Units
Geom File=g01
Flow File=f01
Plan File=p01
Background Map Layer=Inundation Boundary (01pct Value_0)
BEGIN DESCRIPTION:
Stream Name: Laurel Creek (Upper Reach)
Flood Zone: Approximate
Monroe County, West Virginia
HEC-RAS Version: 5.0.7
Vertical Datum: NAVD88
Projection: NAD 1983 StatePlane West Virginia S FIPS 4702 (US Feet)
LiDAR: 2016, 1-meter
Land Use: 2016 NLCD
Hydrology Method:
Regression.
Model Notes:Stream is in karst in the downstream and is removed
END DESCRIPTION:
DSS Export Rating Curves= 0
DSS Export Rating Curve Sorted= 0
DSS Export Volume Flow Curves= 0
DXF OffsetX= 0
DXF OffsetY= 0
DXF ScaleX= 0
DXF ScaleY= 0

--- LAURELCK1.p01 (plan) ---

Plan Title=Floodplain
Program Version=5.07
Short Identifier=Floodplain
Geom File=g01
Flow File=f01
Subcritical Flow
K Sum by GR= 0
Std Step Tol= 0.01
Critical Tol= 0.01
Num of Std Step Trials= 20
Max Error Tol= 0.3
Flow Tol Ratio= 0.001
Split Flow NTrial= 30
Split Flow Tol= 0.02
Split Flow Ratio= 0.02
Log Output Level= 0
Friction Slope Method= 1
Unsteady Friction Slope Method= 2
Unsteady Bridges Friction Slope Method= 1
Parabolic Critical Depth
Global Vel Dist= 0 , 0 , 0
Global Log Level= 0
CheckData=True
Encroach Param=-1 ,0,0, 0
Mapping Interval=1HOUR
Computation Time Step Use Courant=        0
Computation Time Step Use Time Series=    0
Computation Time Step Count To Double=0
Computation Time Step Max Doubling=0
Computation Time Step Max Halving=0
Computation Time Step Residence Courant=0
Run HTab= 0
Run UNet= 0
Run Sediment= 0
Run PostProcess= 0
Run WQNet= 0
Run RASMapper=-1
UNET Theta= 0
UNET Theta Warmup= 0
UNET ZTol= 0
UNET ZSATol= 0
UNET MxIter= 0
UNET Max Iter WO Improvement= 0
UNET MaxInSteps= 0
UNET DtIC= 0
UNET DtMin= 0
UNET MaxCRTS= 0
UNET WFStab= 0
UNET SFStab= 0
UNET WFX= 1
UNET SFX= 1
UNET 1D Methodology=Finite Difference
UNET DSS MLevel= 1
UNET Pardiso=0
UNET DZMax Abort= 0
UNET Use Existing IB Tables= 0
UNET Froude Reduction=False
UNET Froude Limit= 0
UNET Froude Power= 0
UNET D1 Cores= 0
UNET D2 Coriolis=0
UNET D2 Cores= 0
UNET D2 Theta= 1
UNET D2 Theta Warmup= 1
UNET D2 Z Tol= 0.01
UNET D2 Volume Tol= 0.01
UNET D2 Max Iterations= 20
UNET D2 Equation= 0
UNET D2 RampUpFraction=0.1
UNET D2 TimeSlices= 1
UNET D2 BCVolumeCheck=0
UNET D1D2 MaxIter= 0
UNET D1D2 ZTol=0.01
UNET D1D2 QTol=0.1
UNET D1D2 MinQTol=1
Write IC File= 0
Write IC File at Fixed DateTime=0
Write IC File at Sim End=0
Echo Input=False
Echo Parameters=False
Echo Output=False
Write Detailed= 0
HDF Write Warmup=0
HDF Write Time Slices=0
HDF Flush=0
HDF Face Node Velocities=0
HDF Compression= 1
HDF Chunk Size= 1
HDF Spatial Parts= 1
HDF Use Max Rows=0
HDF Fixed Rows= 1
Calibration Method= 0
Calibration Iterations= 20
Calibration Max Change=0.05
Calibration Tolerance=0.2
Calibration Maximum=1.5
Calibration Minimum=0.5
Calibration Optimization Method= 1
WQ AD Non Conservative
WQ ULTIMATE=-1
WQ Max Comp Step=1HOUR
WQ Output Interval=15MIN
WQ Output Selected Increments= 0
WQ Output face flow=0
WQ Output face velocity=0
WQ Output face area=0
WQ Output face dispersion=0
WQ Output cell volume=0
WQ Output cell surface area=0
WQ Output cell continuity=0
WQ Output cumulative cell continuity=0
WQ Output face conc=0
WQ Output face dconc_dx=0
WQ Output face courant=0
WQ Output face peclet=0
WQ Output face adv mass=0
WQ Output face disp mass=0
WQ Output cell mass=0
WQ Output cell source sink temp=0
WQ Output nsm pathways=0
WQ Output nsm derived pathways=0
WQ Output MaxMinRange=-1
WQ Daily Max Min Mean=-1
WQ Daily Range=0
WQ Daily Time=0
WQ Create Restart=0
WQ Fixed Restart=0
WQ System Summary=0
WQ Write To DSS=0
WQ Use Fixed Temperature=0
Sorting and Armoring Iterations= 10
XS Update Threshold= 0.02
Bed Roughness Predictor= 0
Hydraulics Update Threshold= 0.02
Energy Slope Method= 1
Volume Change Method= 1
Sediment Retention Method= 0
XS Weighting Method= 0
Number of US Weighted Cross Sections= 1
Number of DS Weighted Cross Sections= 1
Upstream XS Weight=0
Main XS Weight=1
Downstream XS Weight=0
Number of DS XS's Weighted with US Boundary= 1
Upstream Boundary Weight= 1
Weight of XSs Associated with US Boundary= 0
Number of US XS's Weighted with DS Boundary= 1
Downstream Boundary Weight= 0.5
Weight of XSs Associated with DS Boundary= 0.5
Percentile Method= 0
Sediment Output Level= 3
Mass or Volume Output= 0
Output Increment Type= 1
Profile and TS Output Increment= 1
XS Output Flag= 0
XS Output Increment= 10
Write Gradation File= 0
Read Gradation Hotstart= 0
Write HDF5 File= 1
Write Binary Output= 1
Write DSS Sediment File= 0
SV Curve= 0
Specific Gage Flag= 0

--- LAURELCK1.f01 (steady flow) ---

Flow Title=Flow
Program Version=5.07
Number of Profiles= 6
Profile Names=01pct,10pct,04pct,02pct,0_2pct,01plus
River Rch & RM=LAURELCK1,Main            ,25164
     599     317     421     507     836     886
River Rch & RM=LAURELCK1,Main            ,22398
    1040     564     742     888    1440    1540
River Rch & RM=LAURELCK1,Main            ,22073
    1130     614     806     963    1560    1670
River Rch & RM=LAURELCK1,Main            ,19342
    1240     678     888    1060    1710    1840
River Rch & RM=LAURELCK1,Main            ,11551
    1370     749     981    1170    1880    2030
River Rch & RM=LAURELCK1,Main            ,7254
    1480     809    1060    1260    2030    2180
River Rch & RM=LAURELCK1,Main            ,6282
    1640     902    1180    1400    2240    2420
River Rch & RM=LAURELCK1,Main            ,4101
    1820    1000    1310    1550    2480    2690
Boundary for River Rch & Prof#=LAURELCK1,Main            , 1
Up Type= 0
Dn Type= 3
Dn Slope=0.00507
DSS Import GetInterval= 0
DSS Import GetPeak= 0
DSS Import FillOption= 0

--- LAURELCK1.g01 (geometry) ---

Geom Title=Geometry
Program Version=5.07

River Reach=LAURELCK1       ,Main
Reach XY= 30
     2080008.125      211582.228     2077860.284      210056.214
     2078034.051      209713.836     2077904.885      208839.356
      2078399.19      208018.3182078200.81900181206432.748512927
     2078445.872      205835.129     2078259.789      205647.863
     2078277.831      205244.449     2077890.865      205123.992
     2077895.206      204927.377       2077495.9      204795.433
     2077416.473      204973.818     2076891.825      204955.843
     2076654.676      204182.705     2075713.348      204171.735
     2074980.004      204525.042     2074714.072      204314.298
     2074175.183      204539.299     2073973.099      204440.687
     2073213.735      204811.885     2072321.711       204825.41
     2072004.729      204597.909     2070014.603      205368.357
     2069720.332      205190.752     2068954.186      205525.648
     2067042.207      205141.274     2066321.251      204578.731
      2066178.76      203921.136     2065687.365      203778.869

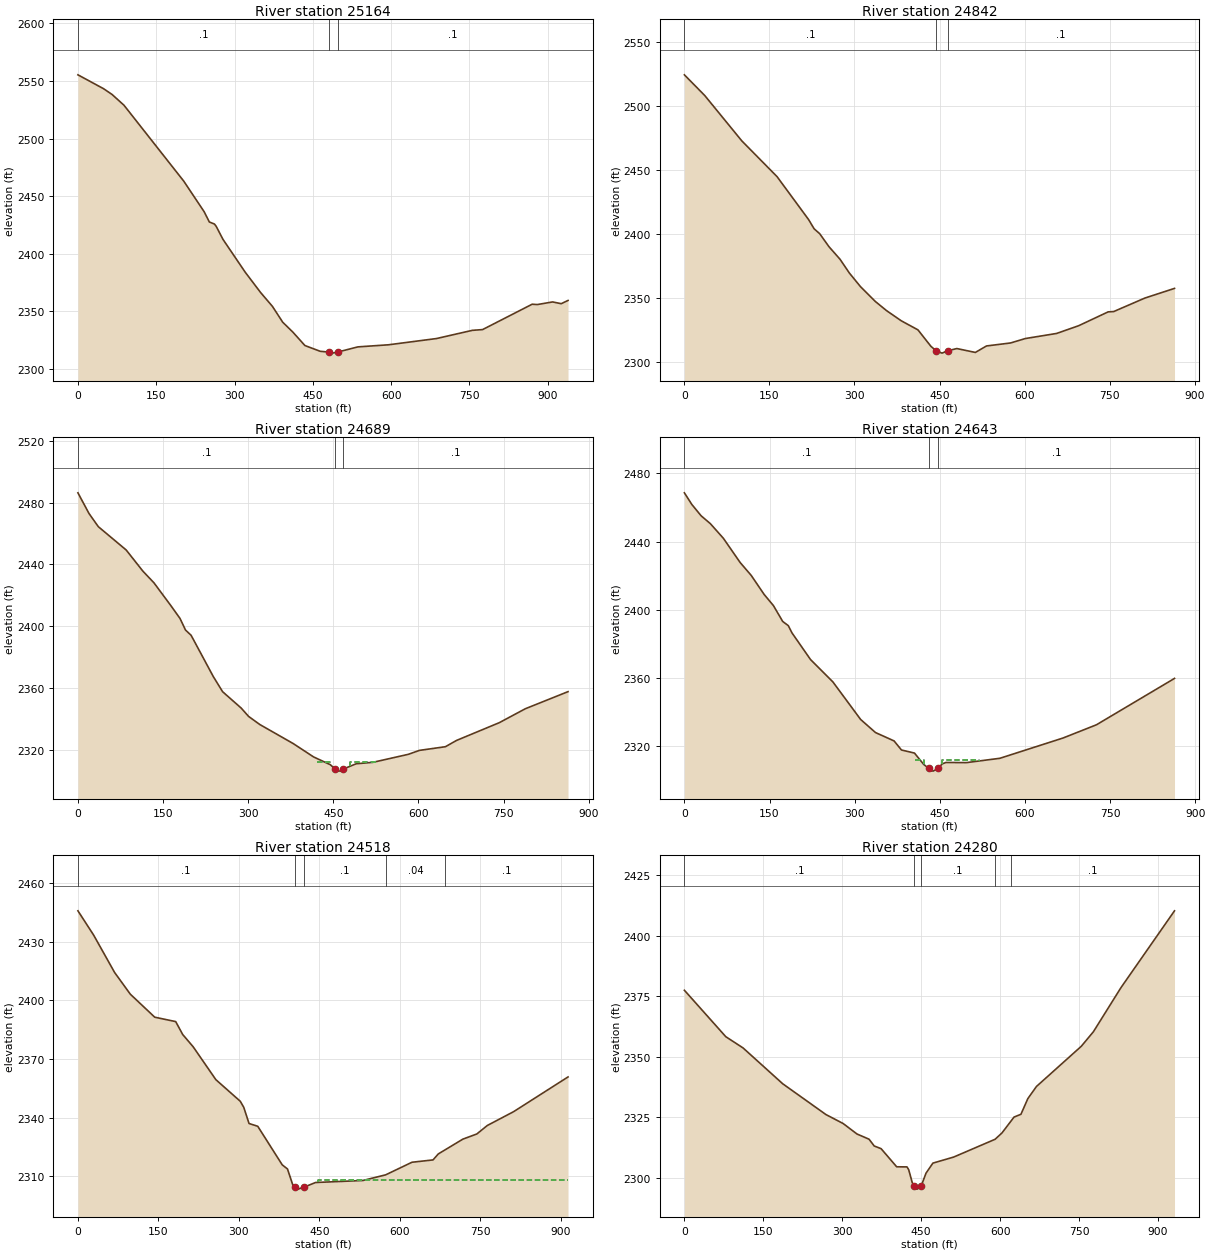
Type RM Length L Ch R = 1 ,25164   ,316.4,321.8,325.7
XS GIS Cut Line= 3
     2080221.584      211143.603     2079998.495      211580.258
     2079761.623       211961.18
#Sta/Elev= 30
       0 2555.33      49 2543.33    65.4 2538.29    88.3 2528.92   202.7 2463.12
   241.9 2436.53   251.7 2427.67   261.5 2425.87   264.8 2423.96   277.9 2412.57
   320.4 2384.14   349.8 2366.56   372.7  2354.4   392.3 2340.72   411.9 2332.05
   434.8 2320.48   464.2 2315.46  480.662314.774   487.1 2313.88  497.462314.774
   536.2 2319.29   595.1 2321.12   686.8 2326.52   755.6 2333.65   775.2  2334.3
   870.2 2356.31     880 2356.02   909.4  2358.3   925.8 2356.77   938.9 2359.58
#Mann= 3 ,-1 , 0
       0      .1       0  480.66    .045       0  497.46      .1       0
Bank Sta=480.66,497.46
XS Rating Curve= 0 ,0
Exp/Cntr=0.3,0.1

Type RM Length L Ch R = 1 ,24842   ,150.7,152.7,151.5
XS GIS Cut Line= 3
     2080070.904      211069.899      2079666.39      211474.413
     2079506.668      211719.205
#Sta/Elev= 30
       0 2524.49      36 2508.29   101.3 2472.91   163.4 2445.02     219 2411.53
   228.8 2404.28   238.6 2400.48     255 2390.31   274.6 2380.45   290.9 2369.79
   310.6  2359.1   336.7 2347.57   356.3 2340.47   382.5 2332.45   411.9 2325.39
   434.8 2312.53  444.182308.956   454.4 2307.21   464.2    2309   480.5 2310.78
   513.2 2307.75   532.8 2312.81   575.3 2315.14   601.3  2318.6   656.5 2322.57
   695.5 2328.64   747.4 2339.42   757.2 2339.67   812.4 2350.24   864.4 2357.75
#Mann= 3 ,-1 , 0
       0      .1       0  444.18    .045       0   464.2      .1       0
Bank Sta=444.18,464.2
XS Rating Curve= 0 ,0
Exp/Cntr=0.5,0.3

Type RM Length L Ch R = 1 ,24689   ,46.7,46.7,46.3
XS GIS Cut Line= 3
     2079998.855      211045.594      2079603.89      211347.243
     2079453.066      211681.445
#Sta/Elev= 30
       0 2486.28    19.6 2472.88      36 2464.38      85 2449.35   114.4 2435.69
     134  2428.1   163.5  2413.5   179.8 2405.14   189.6 2397.58   199.4 2394.22
   238.7 2367.41     255 2357.71   287.7 2347.14   300.8 2341.74   320.4 2336.54
   379.3 2324.22   415.2 2315.58   444.7 2310.56  453.642307.643     461 2306.39
   466.92307.645   490.4 2311.15   519.9 2312.09   582.1 2317.24   601.7 2319.79
   647.6 2322.18   667.2 2326.24   742.5 2337.71   788.3  2346.7   863.6 2357.77
#Mann= 3 ,-1 , 0
       0      .1       0  453.64    .045       0   466.9      .1       0
#XS Ineff= 2 ,-1
  420.56  444.11 2311.98  478.82  524.69 2312.05
Permanent Ineff=
       F       F
Bank Sta=453.64,466.9
XS Rating Curve= 0 ,0
Exp/Cntr=0.5,0.3

Type RM Length L Ch R = 1 ,24643   ,131.8,124.5,116.2
XS GIS Cut Line= 3
     2079957.623      211019.552     2079562.658      211321.201
     2079411.833      211655.403
#Sta/Elev= 30
       0 2468.62    13.1  2461.8    29.4 2455.15    45.8 2450.49    68.7  2441.9
    98.1 2427.73   117.7 2420.11   140.6 2408.87   156.9 2402.34   173.3 2392.99
   183.1 2390.56   189.6  2386.3   222.3 2370.62   261.6 2357.52   310.6  2335.4
   336.8 2327.71   369.5  2322.8   382.5 2317.47   405.4 2315.67   421.8 2308.96
  430.762306.604   438.1 2305.05  447.042306.602   454.5 2309.37     461 2310.14
     497 2310.05   555.9 2312.59   667.2 2324.51   726.1 2332.29   863.6 2359.54
#Mann= 3 ,-1 , 0
       0      .1       0  430.76    .045       0  447.04      .1       0
#XS Ineff= 2 ,-1
  406.96  422.75 2311.72  453.68  519.42 2311.67
Permanent Ineff=
       F       F
Bank Sta=430.76,447.04
XS Rating Curve= 0 ,0
Exp/Cntr=0.5,0.3

Type RM Length L Ch R = 1 ,24518   ,231.4,237.9,237.8
XS GIS Cut Line= 3
     2079857.145      210894.624     2079572.423       211137.68
     2079388.395      211644.624
#Sta/Elev= 30
       0 2445.85    29.3 2433.43    68.4 2414.28    97.7 2403.17   143.2 2391.39
   182.3 2389.13   195.3 2382.54   214.8 2376.25   257.2 2359.39   302.7 2348.33
   309.2 2345.22     319 2336.95   335.3 2335.52   380.9 2315.78   390.7 2313.67
   400.5 2305.56  403.822304.336   410.3 2303.35  421.262304.336     443 2306.74
   531.2 2307.77   573.7 2310.66   622.8 2317.12     662  2318.3   671.8 2321.36
   717.6 2328.94   743.7  2331.6   763.3 2335.95   812.3 2343.02   913.7 2360.79
#Mann= 5 ,-1 , 0
       0      .1       0  403.82    .045       0  421.26      .1       0
  574.36     .04       0  684.36      .1       0
#XS Ineff= 2 , 0
                          447.87         2308.14
Permanent Ineff=
       F       F
Bank Sta=403.82,421.26
XS Rating Curve= 0 ,0
Exp/Cntr=0.3,0.1

Type RM Length L Ch R = 1 ,24280   ,79.6,78.7,77.3
XS GIS Cut Line= 2
     2079648.621        210717.9     2079115.852      211481.789
#Sta/Elev= 30
       0 2377.51    78.7 2358.33   111.5 2353.69   186.9 2338.89   268.9  2326.2
   301.7 2322.48   327.9 2318.17   350.9 2316.01   360.7 2313.22   373.8  2312.1
   403.4 2304.62     423 2304.58   426.3 2303.38   432.9 2298.15  436.952296.586
   442.7  2295.4  449.812296.586   459.1 2301.97   472.2 2306.14   511.6 2308.63
   590.3 2315.97   603.4 2318.58   626.4 2325.15   639.5  2326.3   652.6 2332.76
     669 2337.78   754.2 2354.38   777.2 2360.38   829.7 2378.63   931.3  2410.3
#Mann= 5 ,-1 , 0
       0      .1       0  436.95    .045       0  449.81      .1       0
     590     .04       0     620      .1       0
Bank Sta=436.95,449.81
XS Rating Curve= 0 ,0
Exp/Cntr=0.3,0.1

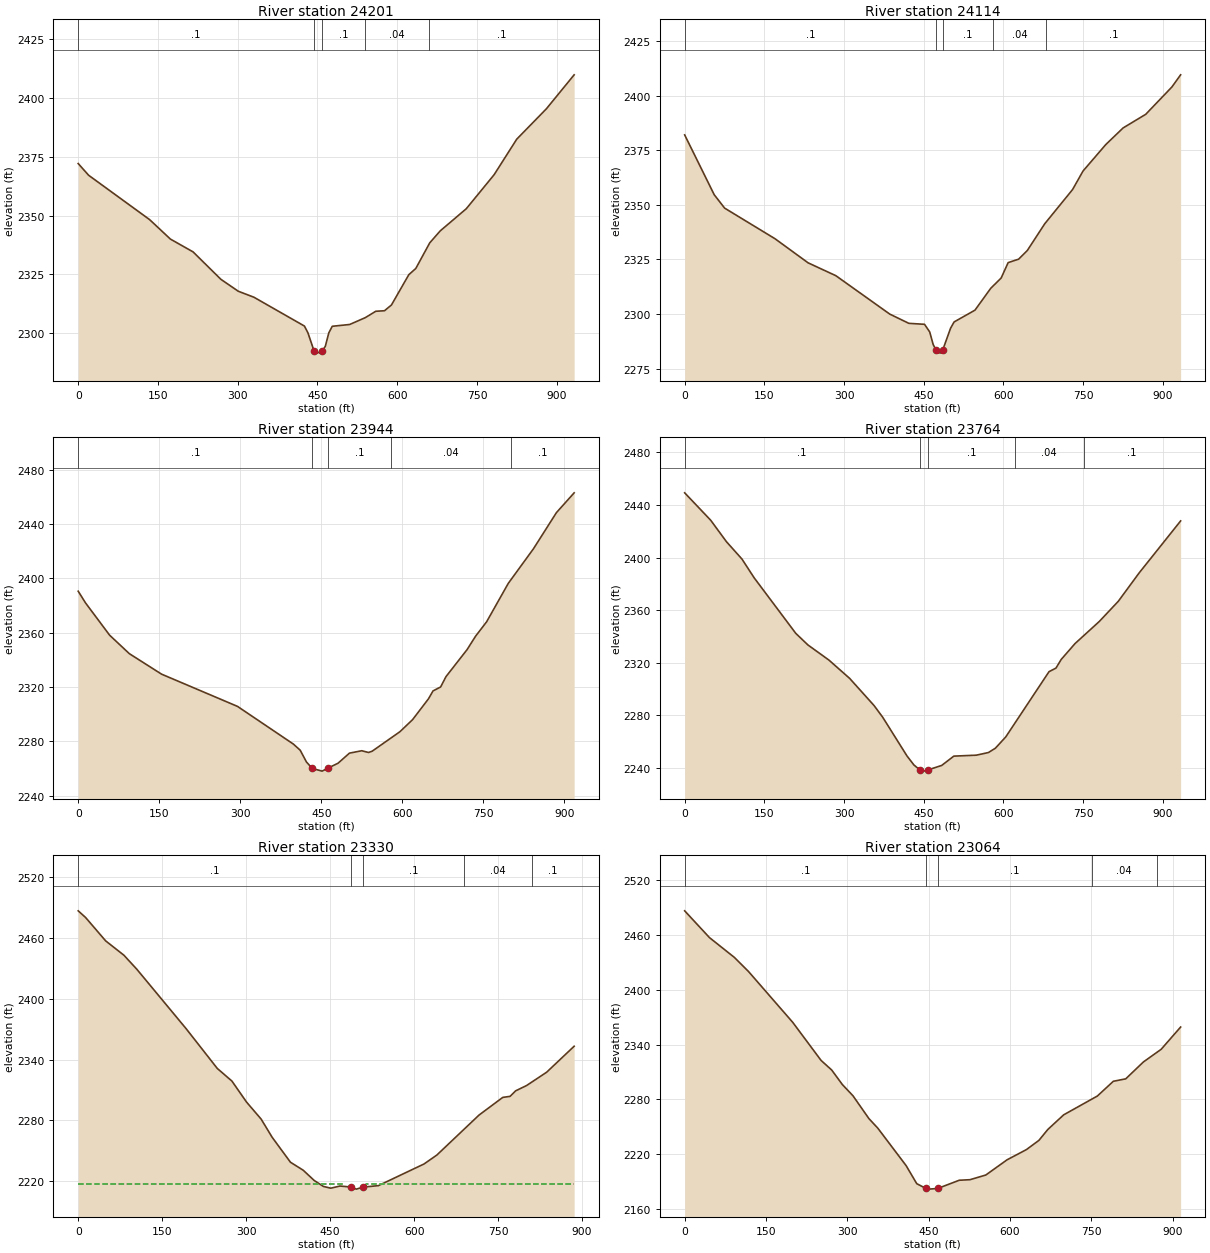
Type RM Length L Ch R = 1 ,24201   ,87.3,87.6,84.6
XS GIS Cut Line= 2
     2079533.603      210646.286     2079108.256      211476.364
#Sta/Elev= 30
       0 2372.15    19.6 2367.17   134.2  2348.3   173.4    2340     216 2334.55
   268.4 2322.86   301.1 2317.79   330.5 2315.24   425.4 2302.98     432 2300.11
  443.41 2292.48   454.9 2291.45     459 2292.48   464.7 2294.32   471.3 2300.09
   477.8 2302.88   510.5 2303.64     540 2306.56   559.6 2309.27     576 2309.49
   589.1 2311.95   621.8 2324.85   634.9 2327.49   661.1 2338.38   680.7 2343.46
   729.8 2352.91   782.2  2367.4   824.7 2382.52   880.4 2395.44   932.7 2409.92
#Mann= 5 ,-1 , 0
       0      .1       0  443.41    .045       0     459      .1       0
     540     .04       0     660      .1       0
Bank Sta=443.41,459
XS Rating Curve= 0 ,0
Exp/Cntr=0.3,0.1

Type RM Length L Ch R = 1 ,24114   ,167.8,169.3,169.9
XS GIS Cut Line= 3
     2079460.963      210609.795     2079241.783      211037.882
     2079099.679      211467.689
#Sta/Elev= 30
       0 2381.98    55.6 2354.61    75.2 2348.48   170.1 2334.46   232.3 2323.44
   284.6 2317.55   386.1 2299.97     422 2295.74   451.5  2295.3   461.3  2291.8
   467.8 2286.04  473.512283.447   480.9 2282.11  485.652283.446   500.6 2293.54
   507.2 2296.38   546.5 2301.78   576.1 2311.76   595.8  2316.5   608.9 2323.53
   628.6 2325.11     645 2329.07   677.8 2341.31   730.2 2356.97   749.9 2365.45
   792.6 2377.53   825.4 2385.18     868 2391.42   917.2 2403.92   933.6 2409.48
#Mann= 5 ,-1 , 0
       0      .1       0  473.51    .045       0  485.65      .1       0
  580.93     .04       0  680.93      .1       0
Bank Sta=473.51,485.65
XS Rating Curve= 0 ,0
Exp/Cntr=0.3,0.1

Type RM Length L Ch R = 1 ,23944   ,180.1,180.7,181.9
XS GIS Cut Line= 4
2079368.64540445210550.5874772592079180.59983493 210856.91977599
2079019.85120293211063.1633038482078853.03658481211308.835741444
#Sta/Elev= 30
       0 2390.52    13.5 2381.93    58.2 2358.12    94.6 2344.55   154.3 2329.45
   294.9  2305.7   398.1 2278.01   410.9 2273.44   422.5 2264.74   433.3 2260.03
   451.4 2258.05   462.4 2260.27     481  2263.9     502 2271.29   524.8 2273.06
   537.3 2271.78   544.1 2272.74   595.5 2287.09   618.9 2295.97   648.3 2311.31
   656.7 2317.11   670.8 2320.03   680.7 2327.64   719.7  2347.5   735.5 2357.43
   755.9 2368.01     796 2396.31   842.6 2421.78   885.1 2448.39   917.9 2462.97
#Mann= 5 ,-1 , 0
       0      .1       0   433.3    .045       0   462.4      .1       0
  579.44     .04       0  800.93      .1       0
Bank Sta=433.3,462.4
XS Rating Curve= 0 ,0
Exp/Cntr(USF)=0,0
Exp/Cntr=0.3,0.1

Type RM Length L Ch R = 1 ,23764   ,428.9,433.7,428.2
XS GIS Cut Line= 3
      2079234.41      210414.019     2079014.639       210808.03
     2078695.918      211170.109
#Sta/Elev= 30
       0 2449.21      49 2428.37    78.5 2412.13   107.9 2398.84   130.8 2384.61
   209.2 2342.38   232.1 2333.57   271.4 2322.14   310.6 2308.16   356.4 2287.59
   372.7  2278.7   418.5 2249.22   431.5  2242.4  442.482238.709   451.2 2237.71
  458.51 2238.71   483.8 2242.04   506.6 2249.11   548.9 2249.83   571.8 2251.84
   584.8 2255.12   604.3 2263.67   685.8 2313.29   698.9 2316.02   708.6 2322.52
   734.7 2334.62   780.4 2351.43   816.2 2366.78   855.3 2388.26   933.5 2427.85
#Mann= 5 ,-1 , 0
       0      .1       0  442.48    .045       0  458.51      .1       0
  621.16     .04       0  751.16      .1       0
Bank Sta=442.48,458.51
XS Rating Curve= 0 ,0
Exp/Cntr=0.3,0.1

Type RM Length L Ch R = 1 ,23330   ,261.9,265.9,265.6
XS GIS Cut Line= 2
     2078879.715      210229.694     2078449.159      211003.999
#Sta/Elev= 30
       0 2486.96    13.1 2480.42      49 2457.31    81.7 2443.09   104.6 2429.34
   192.9  2370.5   248.5 2331.27   274.6 2318.83   300.8 2298.02   326.9 2281.19
   346.5 2263.29   379.2 2238.66   402.1 2230.71   421.7  2220.6   438.1 2214.75
   451.2 2213.03   467.5 2215.15   487.1 2214.21   496.9  2212.1   508.9  2214.1
   536.2 2215.53   617.9 2236.97   640.8  2245.8     716 2285.21   758.5 2302.71
   771.5 2303.71   781.4 2309.15     801 2314.41   836.9 2327.58     886 2353.23
#Mann= 5 ,-1 , 0
       0      .1       0   487.1    .045       0   508.9      .1       0
     690     .04       0     810      .1       0
#XS Ineff= 2 , 0
          473.35 2216.84  514.21         2216.76
Permanent Ineff=
       F       F
Bank Sta=487.1,508.9
XS Rating Curve= 0 ,0
Exp/Cntr=0.3,0.1

Type RM Length L Ch R = 1 ,23064   ,228,230.8,230.8
XS GIS Cut Line= 3
     2078708.569      210119.818     2078449.387      210500.609
     2078186.999       210871.06
#Sta/Elev= 30
       0 2486.56    45.7 2457.24    91.5 2435.62   117.6 2420.19   199.3 2364.42
   251.6  2322.7   271.2 2312.19   290.8 2296.31   310.4 2283.99   339.8    2259
   356.1  2248.6   408.4 2207.52     428 2187.74  445.032182.508   450.8 2181.78
  466.642182.508   506.4 2191.51     526 2192.09   555.3 2197.22   594.5 2213.87
   630.4 2225.13   653.3 2235.18   669.6 2247.04     699 2263.16   761.1 2283.74
   790.5 2299.88   813.4 2302.56     846 2321.06   878.7 2334.89   914.6 2359.27
#Mann= 5 ,-1 , 0
       0      .1       0  445.03    .045       0  466.64      .1       0
  750.63     .04       0  870.63      .1       0
Bank Sta=445.03,466.64
XS Rating Curve= 0 ,0
Exp/Cntr=0.3,0.1

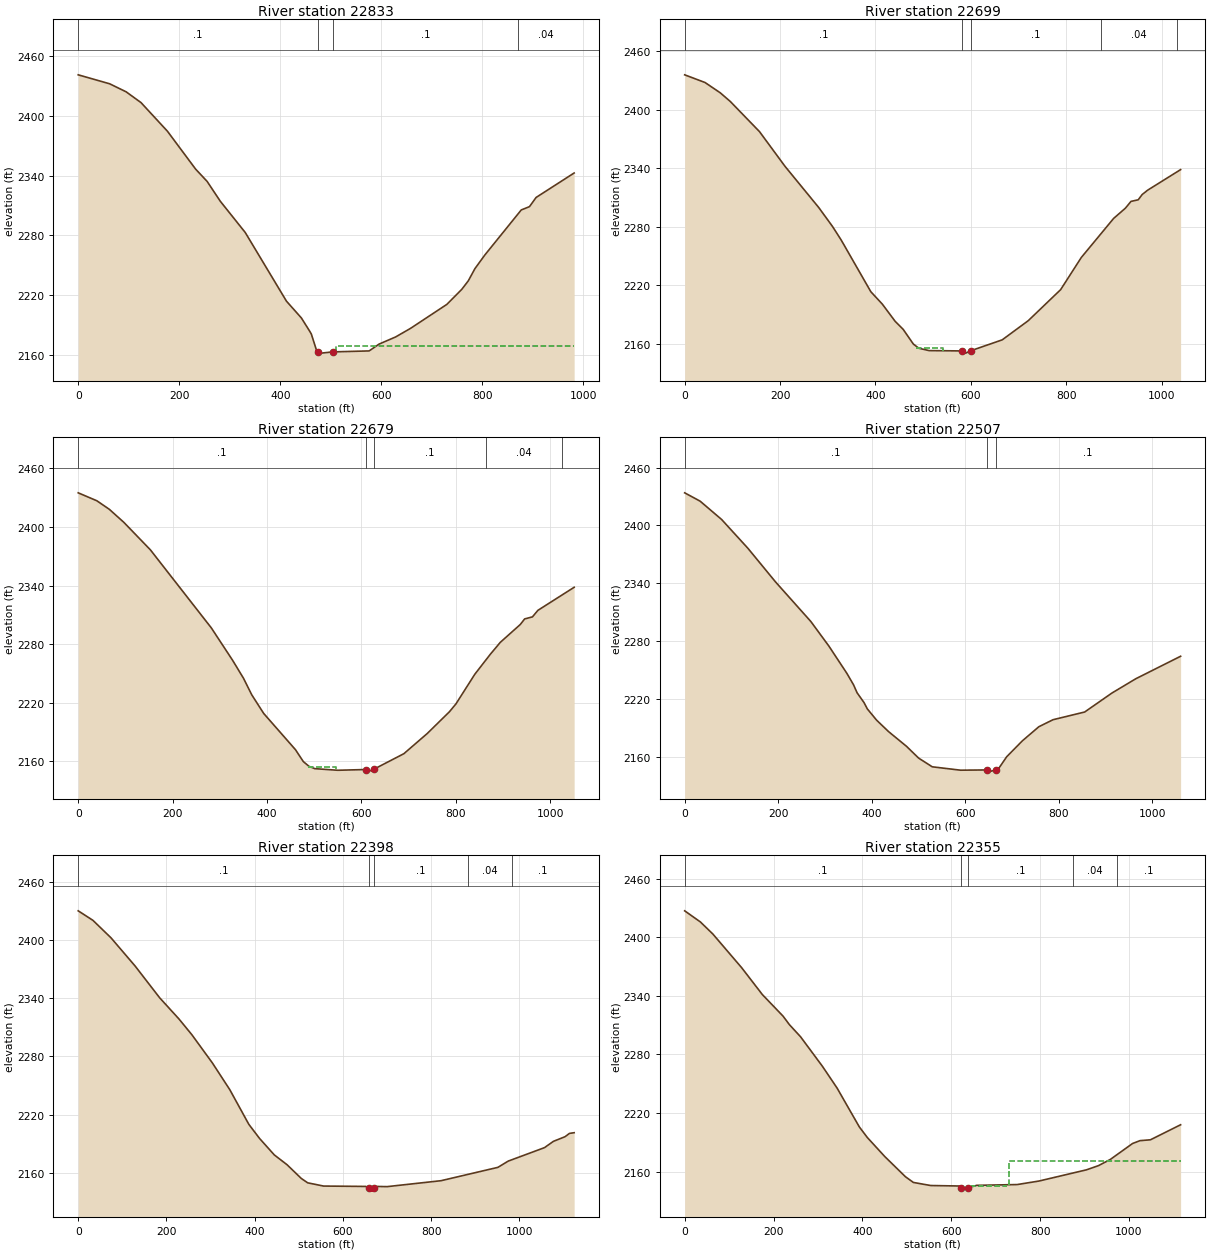
Type RM Length L Ch R = 1 ,22833   ,150.8,134.4,109.3
XS GIS Cut Line= 2
     2078598.465      209972.749     2077963.048      210721.013
#Sta/Elev= 30
       0 2441.38    62.2 2432.38    94.9  2424.3   124.3 2413.49   176.7 2384.68
   232.3 2346.72   255.2 2334.29   281.4 2314.28   330.5 2283.07   412.3 2213.95
   441.8 2197.09   458.1  2183.9   461.4 2181.04   471.2 2165.48   474.5 2162.79
     481 2161.78   503.9 2163.02   575.9    2164   595.5 2170.84   628.3 2178.03
   657.7 2186.61   729.7 2210.74   759.2 2225.83   772.2 2234.43   785.3 2246.68
     805 2260.43     877 2305.63   893.3 2308.96   906.4 2318.18   981.7 2342.76
#Mann= 4 ,-1 , 0
       0      .1       0   474.5    .045       0   503.9      .1       0
     870     .04       0
#XS Ineff= 2 , 0
                          510.51         2168.83
Permanent Ineff=
       F       F
Bank Sta=474.5,503.9
XS Rating Curve= 0 ,0
Exp/Cntr=0.5,0.3

Type RM Length L Ch R = 1 ,22699   ,19.5,19.9,20.5
XS GIS Cut Line= 4
2078582.47358409209970.5181159582078140.43246665210309.891619023
2078176.55625689210375.4848170942077930.34410761210700.598929274
#Sta/Elev= 30
       0 2435.92    42.7 2428.03    74.5  2417.5    95.6  2408.6   156.9 2377.63
   210.6 2341.88     281  2299.8   309.9 2280.35   328.3 2266.29   390.4 2213.28
   414.5 2200.54   441.4 2182.89   458.3  2174.6   479.5  2159.6     491 2155.28
   512.6 2152.84   581.6 2152.52   589.4 2150.26   600.3 2152.77   665.9 2163.89
   720.5 2183.57   788.4 2215.42   831.8 2248.47   899.5 2288.51   924.2 2299.04
   935.9 2305.99   951.1 2307.65   959.4 2313.06     971 2317.56    1040 2338.62
#Mann= 5 ,-1 , 0
       0      .1       0   581.6    .045       0   600.3      .1       0
  872.17     .04       0 1032.17      .1       0
#XS Ineff= 3 ,-1
  485.63  541.24 2155.59  569.49  578.42 2151.85  602.63  611.27 2152.13
Permanent Ineff=
       F       F       F
Bank Sta=581.6,600.3
XS Rating Curve= 0 ,0
Exp/Cntr(USF)=0,0
Exp/Cntr=0.5,0.3

Type RM Length L Ch R = 1 ,22679   ,153.2,172,188.2
XS GIS Cut Line= 4
2078578.73085712209969.3881580952078115.96613342210304.336860945
2078154.86666151210378.096303805 2077918.6568171 210696.42948528
#Sta/Elev= 30
       0 2435.07    39.6 2426.91    65.9  2418.2    96.7 2404.84   152.9  2376.7
   282.1 2296.72   327.2 2263.54   350.2  2245.2   367.7 2228.24   393.2 2209.03
   460.4    2172     477 2159.84   488.8 2155.03   501.3 2152.56   549.9  2150.9
   609.9 2151.66   616.5 2150.02   625.8 2151.77   690.2 2167.89   739.8  2188.6
   786.7 2210.83   800.5 2218.89   840.6 2249.33   873.4 2269.74   894.6 2281.98
   936.8 2300.18   946.1 2305.92   962.6 2308.01   974.3 2314.74    1051 2338.32
#Mann= 5 ,-1 , 0
       0      .1       0   609.9    .045       0   625.8      .1       0
  864.65     .04       0 1024.65      .1       0
#XS Ineff= 3 ,-1
   487.1   545.9 2154.59  599.17  605.99 2151.24  629.42  635.39 2151.24
Permanent Ineff=
       F       F       F
Bank Sta=609.9,625.8
XS Rating Curve= 0 ,0
Exp/Cntr(USF)=0,0
Exp/Cntr=0.5,0.3

Type RM Length L Ch R = 1 ,22507   ,97.9,109.2,117.1
XS GIS Cut Line= 4
2078573.03749686209970.0112467452078074.53504509 210212.42089179
 2077912.2577724 210357.311313832077689.12652246  210539.8732456
#Sta/Elev= 30
       0 2433.78      33 2425.14    78.9 2406.16   135.2 2376.24   194.2 2341.37
   269.6 2300.37   308.3 2274.79   346.8 2246.48   360.8 2234.81   368.6 2226.36
   383.3 2216.26   390.5 2209.63   410.2 2198.02   435.8 2186.12   474.1 2170.87
     500 2158.66   529.2 2149.58   589.8 2146.06   646.12146.323   655.9 2145.09
   664.52146.332   671.2 2147.79   688.3 2159.96   721.9 2176.52   757.1 2191.13
   787.4 2198.42   855.1 2206.41   913.3 2226.07   964.6 2240.97  1060.2 2264.25
#Mann= 3 ,-1 , 0
       0      .1       0   646.1    .045       0   664.5      .1       0
Bank Sta=646.1,664.5
XS Rating Curve= 0 ,0
Exp/Cntr(USF)=0,0
Exp/Cntr=0.3,0.1

Type RM Length L Ch R = 1 ,22398   ,42.7,43.4,42.8
XS GIS Cut Line= 4
2078563.86747712209967.8486651922078035.74188879210208.673933473
2077844.56042581210187.5489099392077495.99753751210230.855208183
#Sta/Elev= 30
       0 2430.68    33.4 2420.82    74.3 2402.77   128.8 2373.68   184.8 2340.61
   228.1 2318.96   257.6 2302.51   303.8 2273.53   343.5 2245.73   386.7 2209.83
   411.1 2195.18   444.4 2178.22   473.3 2168.06   505.7 2153.81   520.1 2149.32
   556.2 2145.98   651.6  2145.6   658.12144.204   660.6 2142.81  670.262144.204
   677.1 2145.58   700.2 2145.39   822.4 2151.53   951.3 2165.35   974.5 2171.78
  1056.8 2185.73    1077 2192.24  1103.4 2197.05  1113.4 2200.46    1124 2201.16
#Mann= 5 ,-1 , 0
       0      .1       0   658.1    .045       0  670.26      .1       0
  882.79     .04       0  982.79      .1       0
Bank Sta=658.1,670.26
XS Rating Curve= 0 ,0
Exp/Cntr(USF)=0,0
Exp/Cntr=0.5,0.3

Type RM Length L Ch R = 1 ,22355   ,41.9,54.9,56.3
XS GIS Cut Line= 4
2078556.05585857209961.4385757832078053.28609409210180.223113063
  2077862.030737210144.0005075532077495.70138515210215.915419628
#Sta/Elev= 30
       02427.231  35.3232415.852  63.3182403.506 128.3512368.877 174.8652341.381
 221.3792319.299 235.6912310.573 260.7382298.177 309.9882267.904 343.0322245.555
 393.124 2205.71 411.0142194.918 450.3722175.353 496.8862154.663 514.7762148.784
 553.7452145.635 617.1892145.146  621.972143.248 630.5462141.938  637.792143.235
 657.2592145.809 748.279 2146.61 797.5742150.232 904.5652161.743 931.3122165.993
  958.062172.3711008.2122188.7281024.9292191.6371048.3332192.5031116.2872207.923
#Mann= 5 ,-1 , 0
       0      .1       0  621.97    .045       0  637.79      .1       0
  872.97     .04       0  972.97      .1       0
#XS Ineff= 3 ,-1
       0   614.9 2143.34  645.37  724.83 2144.98  728.94  1123.4 2171.08
Permanent Ineff=
       F       F       F
Bank Sta=621.97,637.79
XS Rating Curve= 0 ,0
Exp/Cntr(USF)=0,0
Exp/Cntr=0.5,0.3

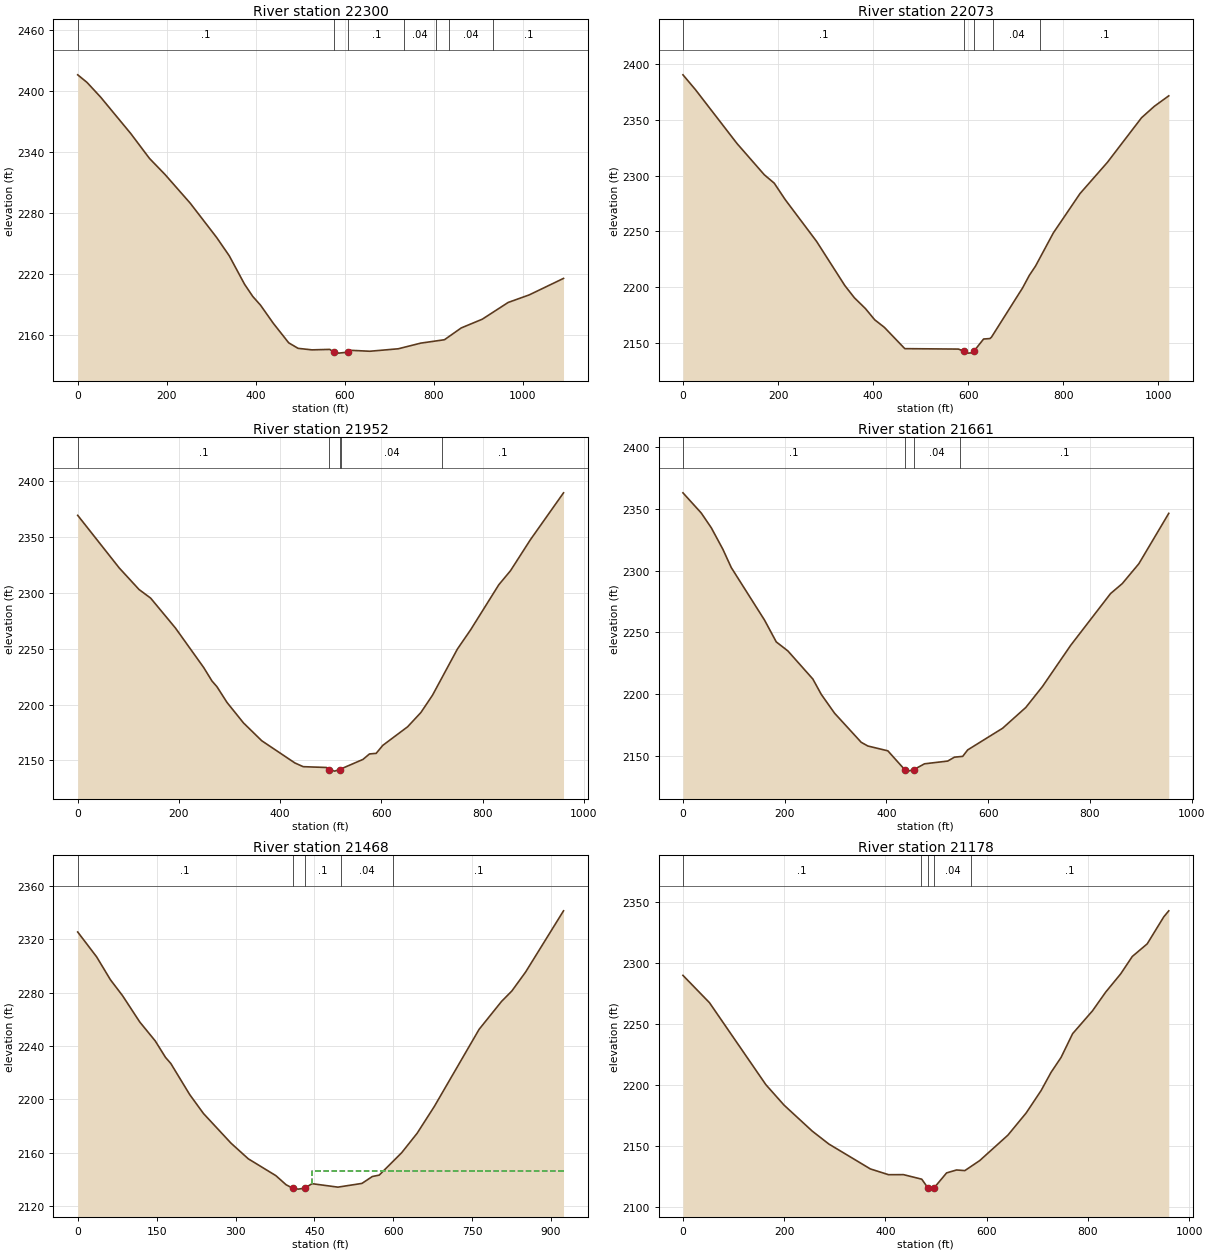
Type RM Length L Ch R = 1 ,22300   ,227.7,226.6,222.6
XS GIS Cut Line= 4
 2078529.9755826209952.7451504612078048.93938143210138.204890671
2077902.53115978210110.3445924022077486.10178615210207.700436968
#Sta/Elev= 30
       0 2415.69    20.8 2408.28    51.5 2393.78   119.3 2357.92   161.5 2333.39
   196.1 2317.76   252.9 2289.47   312.7 2255.51   340.8 2237.63   375.2 2209.64
   393.5 2197.75   411.1 2189.08   439.7 2171.33   474.4 2152.09   495.5 2146.66
   526.6 2145.17   566.7 2145.63  575.642142.952   586.7 2141.96  608.242142.951
   613.4 2144.73   656.8  2143.8   720.8 2146.24   771.3  2151.8   824.5 2155.13
   862.3 2166.75   909.5 2175.31   967.7 2191.79    1015 2199.22  1092.2 2215.46
#Mann= 7 ,-1 , 0
       0      .1       0  575.64    .045       0  608.24      .1       0
  734.58     .04       0  804.58      .1       0  834.58     .04       0
  934.58      .1       0
#XS Ineff= 2 , 0
          570.72 2142.96  615.66         2142.96
Permanent Ineff=
       F       F
Bank Sta=575.64,608.24
XS Rating Curve= 0 ,0
Exp/Cntr(USF)=0,0
Exp/Cntr=0.5,0.3

Type RM Length L Ch R = 1 ,22073   ,120.5,120.8,118
XS GIS Cut Line= 4
2078483.67234189209926.0334565232078006.01208755209995.276589216
2077759.55347967209958.8946042422077469.67121229 209976.49879052
#Sta/Elev= 30
       0 2390.71    25.9 2377.59   113.8 2328.93   171.3 2300.81     192 2293.36
   215.1 2278.57   281.2 2240.96   340.8 2201.16   360.7 2190.31   383.9 2180.61
   403.3 2170.56   423.7 2163.75   466.8 2144.56   579.6 2144.18  591.052142.298
   599.5 2140.54   609.4 2140.85  612.192142.297   632.6 2153.23   645.9 2153.63
   649.2 2154.93   714.6 2199.16   728.8 2210.45     742 2218.91   779.4 2248.65
   835.4 2283.94   893.2 2312.11   964.9 2352.13   991.8 2362.41  1022.2 2371.83
#Mann= 5 ,-1 , 0
       0      .1       0  591.05    .045       0  612.19      .1       0
  652.65     .04       0  751.78      .1       0
Bank Sta=591.05,612.19
XS Rating Curve= 0 ,0
Exp/Cntr(USF)=0,0
Exp/Cntr=0.3,0.1

Type RM Length L Ch R = 1 ,21952   ,290.8,291.5,290.3
XS GIS Cut Line= 2
     2078449.159      209898.097     2077490.826      209849.486
#Sta/Elev= 30
       0 2369.47    81.9 2322.44   121.2 2303.04   144.1 2295.34   193.2 2268.49
   248.9 2233.16   265.3 2221.09   275.1    2216   294.8    2202   327.5 2183.57
   363.5 2167.64     429 2147.74   445.4 2144.42   491.2 2143.69  496.982141.878
   507.6 2140.43  517.162141.876   563.3 2150.88   576.4 2155.81   589.5 2156.33
   602.6 2163.49   651.7 2180.16   677.9 2192.93   700.8  2208.4     750 2249.75
   776.2 2267.04   831.8 2307.33   854.8 2319.84   894.1  2347.6   959.6 2389.63
#Mann= 5 ,-1 , 0
       0      .1       0  496.98    .045       0  517.16      .1       0
     520     .04       0     720      .1       0
Bank Sta=496.98,517.16
XS Rating Curve= 0 ,0
Exp/Cntr=0.3,0.1

Type RM Length L Ch R = 1 ,21661   ,191.7,193,192.7
XS GIS Cut Line= 3
     2078472.722       209608.69     2078028.671      209642.848
     2077519.495      209621.784
#Sta/Elev= 30
       0 2362.98      36 2346.62    55.7 2334.69    78.6 2317.19      95 2302.46
   160.5 2259.87   183.4 2242.32   206.3 2234.98   255.4 2212.22   271.8 2199.89
     298 2184.61   350.4 2161.03   363.5 2158.03   402.8 2154.13  436.132138.804
   442.1  2137.7  453.342138.804   474.8 2143.62   520.5 2145.85   533.6 2148.99
   549.9 2149.65   559.7 2154.87   628.3 2172.39     674 2189.26   706.7 2206.19
   762.2 2239.54   840.6 2281.45   863.5 2289.46   896.2 2305.58     955 2346.38
#Mann= 4 ,-1 , 0
       0      .1       0  436.13    .045       0  453.34     .04       0
  545.36      .1       0
Bank Sta=436.13,453.34
XS Rating Curve= 0 ,0
Exp/Cntr=0.3,0.1

Type RM Length L Ch R = 1 ,21468   ,289.9,290.1,286.5
XS GIS Cut Line= 2
     2078431.798      209448.444     2077508.187      209453.652
#Sta/Elev= 30
       0  2325.4      36 2306.75    62.2 2289.59    85.2 2277.67   117.9 2257.95
   147.4  2243.7     167  2231.3   176.9 2226.84   212.9 2203.48   239.1 2189.25
   291.5    2167   324.2 2155.31   376.7 2142.66   396.3 2135.79  408.582133.299
   419.2 2132.54  432.142133.299   445.4 2136.63   494.6 2134.03   540.4 2136.83
   560.1    2142   573.2 2143.05   615.8  2159.8   645.2 2174.38     678 2194.56
   763.1 2252.38   805.7 2273.29   825.4 2281.17   851.6 2295.42   923.6 2341.28
#Mann= 5 ,-1 , 0
       0      .1       0  408.58    .045       0  432.14      .1       0
     500     .04       0     600      .1       0
#XS Ineff= 2 , 0
                          445.56         2145.81
Permanent Ineff=
       F       F
Bank Sta=408.58,432.14
XS Rating Curve= 0 ,0
Exp/Cntr=0.3,0.1

Type RM Length L Ch R = 1 ,21178   ,75.7,75.9,72.7
XS GIS Cut Line= 2
     2078400.548      209255.736     2077443.951      209175.874
#Sta/Elev= 30
       0 2290.09    52.4  2267.7   163.8  2200.5   199.8  2183.7   255.5  2162.4
   288.3 2151.82   370.2 2131.43   406.2 2126.68   435.7 2126.73   471.8    2123
  483.732116.025   488.2 2114.85  496.462116.023   520.9 2128.14   540.6 2130.55
     557 2130.04   586.4 2138.27   642.1 2159.12   678.2 2177.33   707.7 2195.71
   727.3 2210.57     747 2222.76   769.9 2242.28   809.2 2261.04   835.4 2276.45
   864.9 2291.33   887.8 2305.58   917.3 2315.94   950.1 2338.12   959.9 2343.01
#Mann= 5 ,-1 , 0
       0      .1       0     470     .04       0  483.73    .045       0
  496.46     .04       0     570      .1       0
Bank Sta=483.73,496.46
XS Rating Curve= 0 ,0
Exp/Cntr=0.3,0.1

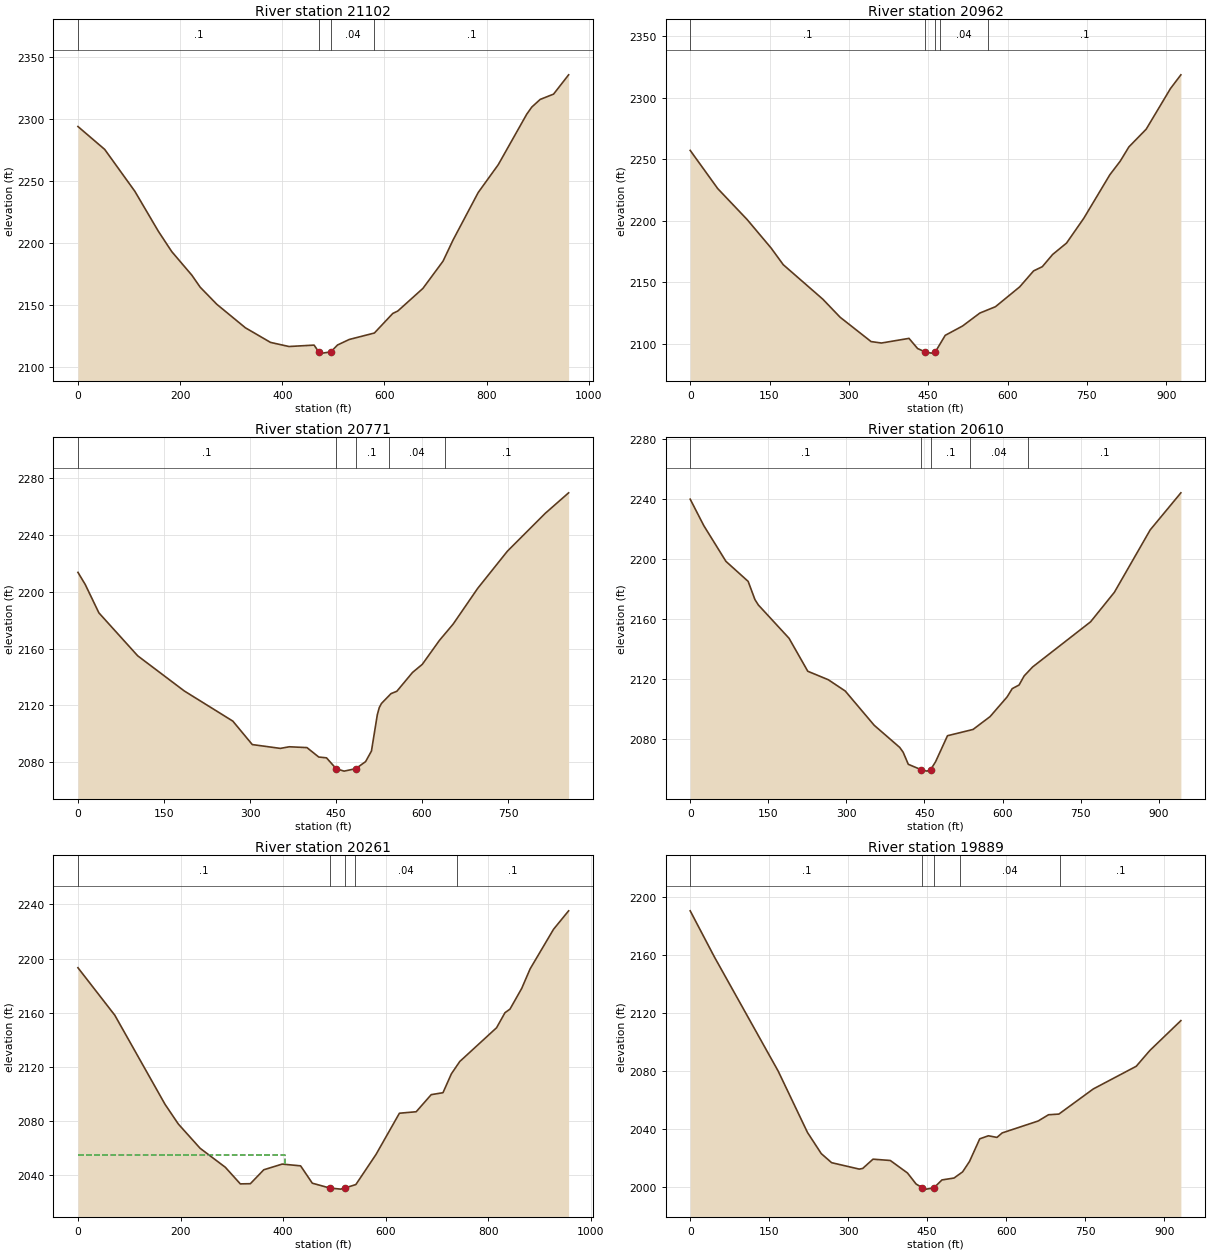
Type RM Length L Ch R = 1 ,21102   ,138.8,140.1,135.2
XS GIS Cut Line= 2
     2078411.182      209161.913     2077451.546      209124.153
#Sta/Elev= 30
       0 2293.74    52.4 2275.32   111.4 2241.64   157.3 2209.57   183.6 2193.16
   222.9 2174.22   239.3 2164.52     272 2150.72   327.8 2131.88   376.9 2120.15
     413 2116.84   462.2 2117.97  471.282112.514   478.6 2111.52  494.932112.514
     508 2118.04     531  2122.5   580.2 2127.68   616.2 2143.42     626 2145.37
   675.2 2163.56   714.6 2185.47   734.2 2202.48   783.4 2240.66   822.7 2263.06
   878.4 2303.64   888.3 2309.38   904.7 2315.53   930.9 2319.79   960.4 2335.31
#Mann= 4 ,-1 , 0
       0      .1       0  471.28    .045       0  494.93     .04       0
     580      .1       0
Bank Sta=471.28,494.93
XS Rating Curve= 0 ,0
Exp/Cntr=0.3,0.1

Type RM Length L Ch R = 1 ,20962   ,181.1,190.4,196.2
XS GIS Cut Line= 3
     2078400.127      209033.055     2077947.442      209024.124
     2077472.662      209010.256
#Sta/Elev= 30
       0 2257.28    52.1 2226.18   107.5 2201.09   153.1 2177.77   175.9  2164.3
   250.8  2136.2   283.4 2121.56     342 2101.73   361.6 2100.55   413.7 2104.34
     430 2096.06   444.32093.286     456 2092.33  463.412093.287   482.2  2106.8
     515  2114.4   547.8 2124.96   577.2 2130.09   623.1 2146.28   649.3 2159.24
   665.7 2162.64   685.4 2172.64   711.6 2181.88   744.3 2202.11   793.4  2237.4
   813.1 2248.53   829.5 2260.12   862.2 2274.54   908.1 2307.58   927.8 2318.77
#Mann= 5 ,-1 , 0
       0      .1       0   444.3    .045       0  463.41      .1       0
  472.77     .04       0  562.77      .1       0
Bank Sta=444.3,463.41
XS Rating Curve= 0 ,0
Exp/Cntr=0.3,0.1

Type RM Length L Ch R = 1 ,20771   ,153.5,160.8,168.3
XS GIS Cut Line= 4
 2078355.6257235 208967.365101642078034.12845949208885.474289108
2077767.22507049208809.649462689 2077521.5526329208791.451504349
#Sta/Elev= 30
       0 2213.62    12.8 2205.02    36.5 2185.15   104.2 2154.92   185.5 2130.18
   270.1 2108.98     304 2092.49   352.9  2089.8   368.6 2090.94   399.3 2090.36
   419.9 2083.72   433.4 2083.16   450.4 2075.47   464.1 2073.81   484.5 2075.54
   501.6 2080.51   511.8 2087.96     522 2113.43   525.4 2118.46   529.2 2121.39
   545.9 2128.32   556.1    2130   583.4 2143.22   600.5 2148.95   630.4 2165.81
   654.2 2177.21     697 2202.34   748.8  2228.5   814.6 2255.06   855.6 2269.57
#Mann= 5 ,-1 , 0
       0      .1       0   450.4    .045       0   484.5      .1       0
  541.76     .04       0  639.23      .1       0
Bank Sta=450.4,484.5
XS Rating Curve= 0 ,0
Exp/Cntr(USF)=0,0
Exp/Cntr=0.3,0.1

Type RM Length L Ch R = 1 ,20610   ,337.2,349.2,336.7
XS GIS Cut Line= 3
     2078438.515      208891.081     2078011.158      208755.116
     2077583.622      208507.167
#Sta/Elev= 30
       0 2239.84    26.2 2222.17    68.7 2198.39   111.3 2185.08   124.4 2172.92
   130.9 2169.36   189.9 2147.15   225.9 2125.18   265.2 2119.55   297.9    2112
   353.5 2089.18   402.6 2074.41   409.2 2071.17     419 2063.18  443.792059.568
     455 2058.63  461.87 2059.57   471.4 2064.88   494.3 2082.22   543.4  2086.4
   576.1 2094.96   608.8 2108.06   618.7  2113.6   631.8 2116.02   641.6 2122.07
   657.9 2128.06   769.2 2158.12     815 2177.84   883.8  2219.4   942.7 2244.08
#Mann= 5 ,-1 , 0
       0      .1       0  443.79    .045       0  461.87      .1       0
  538.46     .04       0  648.46      .1       0
Bank Sta=443.79,461.87
XS Rating Curve= 0 ,0
Exp/Cntr=0.3,0.1

Type RM Length L Ch R = 1 ,20261   ,364.6,372.4,372.5
XS GIS Cut Line= 3
     2078522.848      208662.711     2078059.572      208451.756
     2077613.313      208420.254
#Sta/Elev= 30
       0 2193.21    71.8  2158.1   169.7  2092.2   195.8 2077.53   238.2 2059.62
   287.2 2045.62   316.5  2033.3   336.1 2033.45   362.2 2043.74   398.1 2047.96
     434 2046.65   456.8 2033.82  490.822030.242   512.3 2029.43  520.312030.242
   541.7 2032.82   580.9 2055.04   626.6 2085.58   659.3 2086.68   688.6 2099.33
   711.5 2100.76   727.8 2114.68   744.2 2123.83     816 2148.84   832.3 2159.93
   842.1  2162.6     865 2177.94   881.3 2192.32     927 2221.66   956.4 2235.31
#Mann= 5 ,-1 , 0
       0      .1       0  490.82    .045       0  520.31      .1       0
  539.04     .04       0  739.04      .1       0
#XS Ineff= 2 , 0
          403.62 2054.38
Permanent Ineff=
       F       F
Bank Sta=490.82,520.31
XS Rating Curve= 0 ,0
Exp/Cntr=0.3,0.1

Type RM Length L Ch R = 1 ,19889   ,219.8,216.4,207.3
XS GIS Cut Line= 3
      2078681.57      208409.162        2078280.      208201.847
     2077867.312      207957.116
#Sta/Elev= 30
       0 2190.75    45.8 2159.02     167  2080.2   222.7 2037.83   248.9 2023.22
   268.5 2016.99   320.9 2012.56   327.5    2013   347.1  2019.4   379.9 2018.51
   412.6 2009.87     429 2002.24  440.911999.664   448.6 1998.74  462.851999.663
     478 2005.08   500.9 2006.39   517.2 2010.63   530.3  2017.8   549.8 2033.45
   566.2 2035.54   582.5 2034.42   592.3 2037.51   660.8 2045.76   680.4 2050.06
     700 2050.51   765.3 2067.84   846.9 2083.49     873 2094.48   931.7 2114.99
#Mann= 5 ,-1 , 0
       0      .1       0  440.91    .045       0  462.85      .1       0
  511.93     .04       0  701.93      .1       0
Bank Sta=440.91,462.85
XS Rating Curve= 0 ,0
Exp/Cntr=0.3,0.1