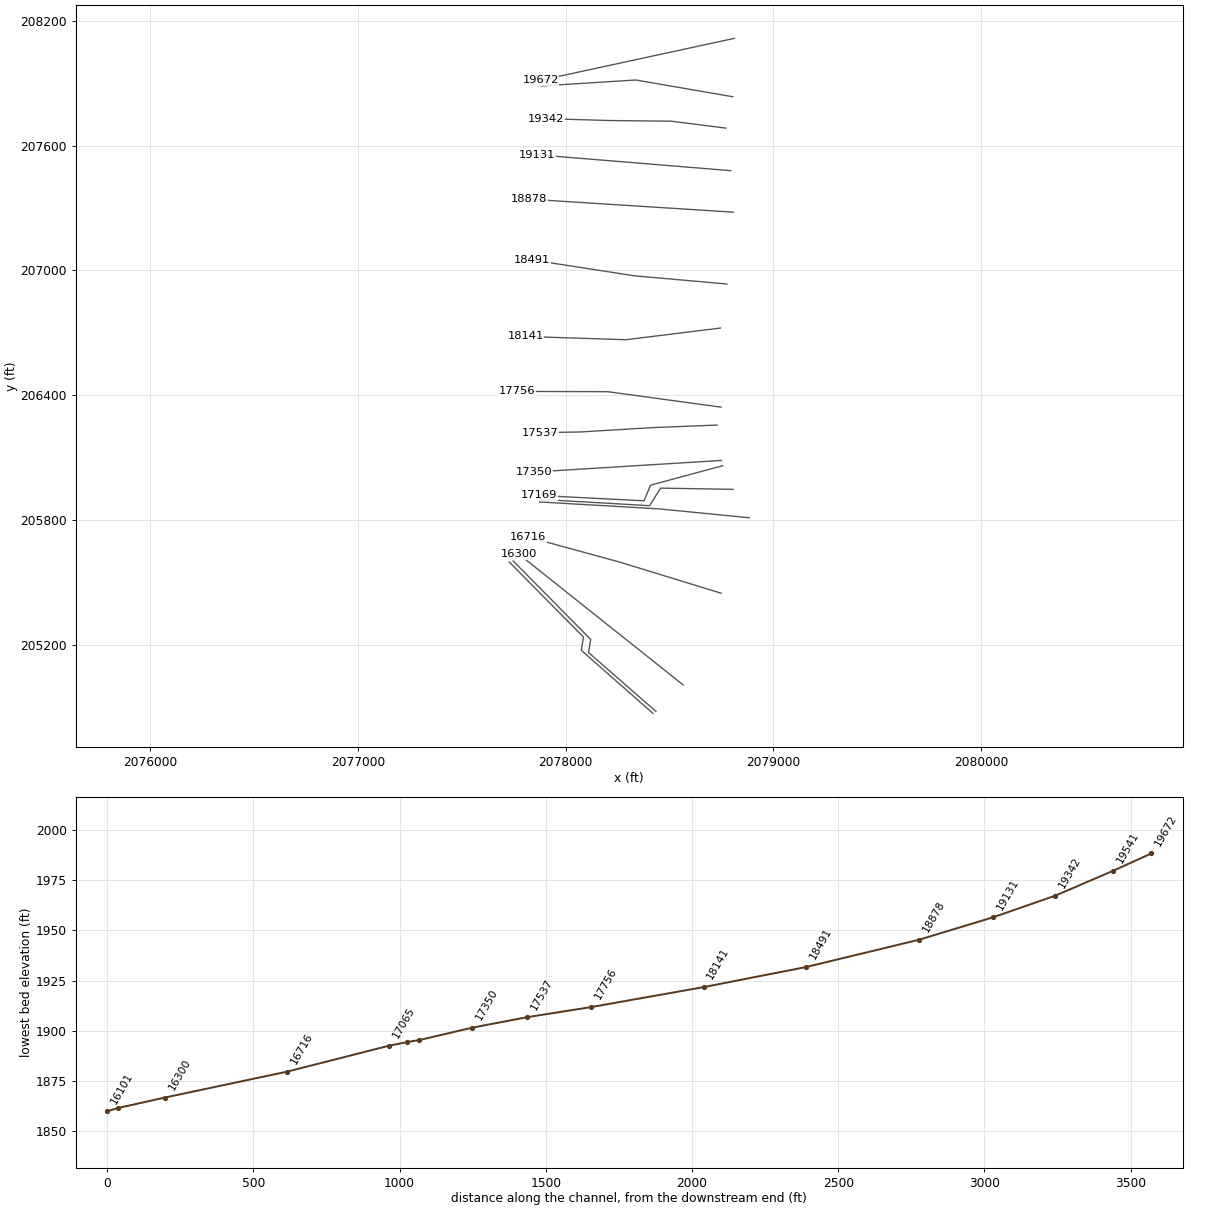
HEC-RAS study LAURELCK1.prj: LAURELCK1

--- LAURELCK1.g01 (geometry) --- (continued)

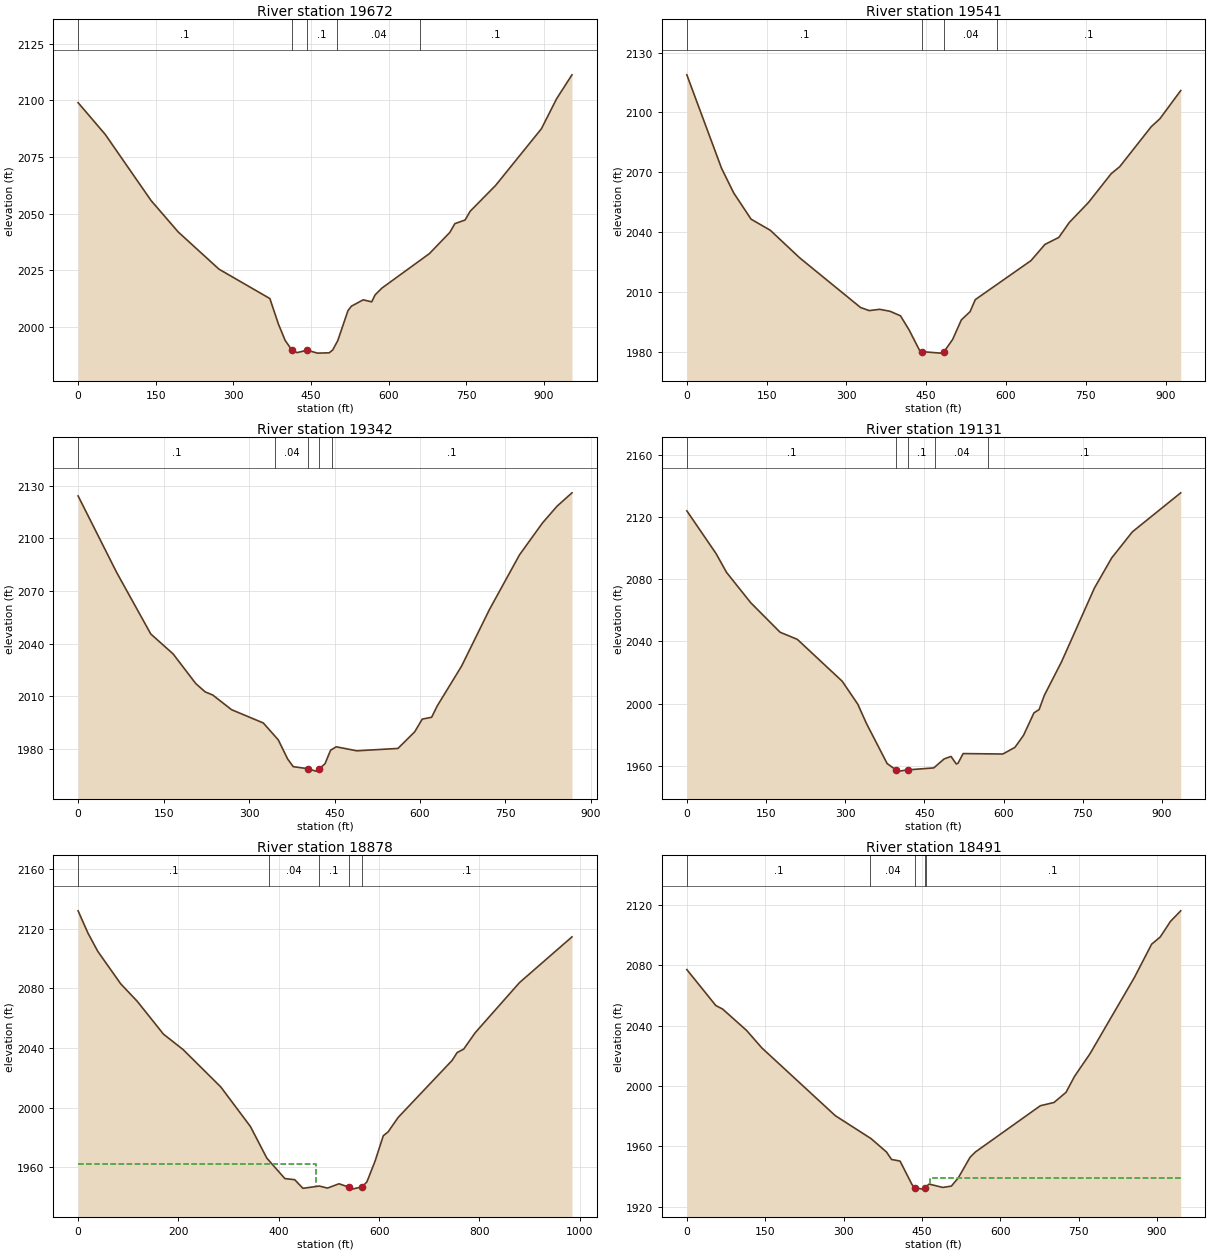
Type RM Length L Ch R = 1 ,19672   ,129.6,131.6,122.1
XS GIS Cut Line= 2
     2078812.223       208116.34     2077879.932      207914.517
#Sta/Elev= 30
       0 2099.03    52.4 2084.99     141 2055.72   193.4 2041.83   272.1 2025.38
   370.4 2012.38   386.8 2001.15   399.9 1993.87     413 1989.54   422.9 1988.47
   442.5 1989.53   462.2 1988.24   485.1 1988.38   491.7 1989.63   501.5 1993.76
   521.2 2007.02   527.8    2009   550.7 2011.82   567.1 2010.92   573.6 2013.99
   586.8 2017.01   678.5 2032.26   717.9 2041.63   727.7 2045.52   747.4 2047.12
   757.2 2050.99   806.4 2062.43   894.9 2087.52   924.4 2100.86   953.9 2111.35
#Mann= 5 ,-1 , 0
       0      .1       0     413    .045       0   442.5      .1       0
     500     .04       0     660      .1       0
Bank Sta=413,442.5
XS Rating Curve= 0 ,0
Exp/Cntr=0.3,0.1

Type RM Length L Ch R = 1 ,19541   ,190.9,198.3,197.6
XS GIS Cut Line= 3
      2078804.16      207835.353     2078337.514      207915.951
     2077883.332      207887.325
#Sta/Elev= 30
       0 2118.84    65.3 2072.04    88.2 2059.69   120.8  2046.6   156.8 2041.07
   212.3 2027.22   326.6  2002.4   342.9 2000.84   362.5 2001.49   382.1  2000.5
   401.7 1998.24     418 1991.13   437.6 1980.92  442.33 1980.31   476.8 1979.56
  483.721980.309   499.8 1986.42   516.1 1996.18   532.5  2000.3   542.3 2006.33
   647.1 2025.86   673.3 2033.96   699.5 2037.49   719.1 2044.95   755.1 2054.94
   797.7 2069.32     814  2072.9     873 2092.83   889.4 2096.85   928.6 2110.96
#Mann= 4 ,-1 , 0
       0      .1       0  442.33    .045       0  483.72     .04       0
  583.56      .1       0
Bank Sta=442.33,483.72
XS Rating Curve= 0 ,0
Exp/Cntr=0.3,0.1

Type RM Length L Ch R = 1 ,19342   ,212.7,211.7,210.3
XS GIS Cut Line= 4
2078771.14577227207684.4090386382078507.27537634207717.771962263
2078216.10804289207720.804955319 2077906.7427511207729.903934489
#Sta/Elev= 30
       0 2124.26    67.6 2080.61   127.5 2045.47   166.8 2034.05   206.5 2017.14
     223 2012.39   236.2 2010.63   269.3 2002.23     325 1994.65   351.3    1985
   367.7  1974.1   377.5 1969.72   403.3 1968.55   416.9 1967.16   423.5 1968.54
   433.3  1971.4   443.1 1979.11     453 1981.04   489.1 1978.76   561.3 1980.12
   590.8 1989.64   603.9 1996.86   620.4 1997.91   630.2 2004.37   672.9 2027.08
   722.1 2059.56   774.6 2090.63   815.1  2108.9   840.6 2118.44   866.7 2126.03
#Mann= 5 ,-1 , 0
       0      .1       0  345.97     .04       0   403.3    .045       0
   423.5     .04       0  445.97      .1       0
Bank Sta=403.3,423.5
XS Rating Curve= 0 ,0
Exp/Cntr(USF)=0,0
Exp/Cntr=0.3,0.1

Type RM Length L Ch R = 1 ,19131   ,252.3,252.5,255.9
XS GIS Cut Line= 2
     2078794.645      207479.694     2077862.354      207556.083
#Sta/Elev= 30
       0 2124.19    55.6 2096.52    75.2 2084.52     121 2064.98   176.6 2045.97
   209.3 2041.36   294.4 2014.33   323.8 1999.58   340.2 1987.14   379.4 1961.32
  395.981957.258   402.3 1956.45  418.511957.259   467.7 1958.53   487.3 1964.31
   500.4 1965.91   510.2 1961.11   513.5 1961.48   523.3 1967.76   598.5 1967.48
   621.4 1971.77   637.8 1979.59   657.4 1993.99   667.2 1996.12     677 2005.24
   709.7 2026.92   771.9  2074.4   804.6 2093.81   843.8 2110.65   935.4  2135.8
#Mann= 5 ,-1 , 0
       0      .1       0  395.98    .045       0  418.51      .1       0
     470     .04       0     570      .1       0
Bank Sta=395.98,418.51
XS Rating Curve= 0 ,0
Exp/Cntr=0.3,0.1

Type RM Length L Ch R = 1 ,18878   ,383.5,387.3,384.4
XS GIS Cut Line= 2
     2078806.798      207280.041     2077824.159      207342.541
#Sta/Elev= 30
       0 2132.12    19.6  2117.2    39.2 2104.94      85  2083.1   117.8 2071.44
   170.1 2049.37   209.4 2038.96   284.6 2013.85   343.5 1987.37   376.2 1966.14
   412.2 1952.41   431.8 1951.65   448.2 1945.87   480.9 1947.39   497.2 1946.02
   520.1 1948.91   539.7 1946.67   546.3 1945.32   565.9 1946.84   575.7 1950.14
   592.1 1964.18   608.4 1981.15   618.2  1983.8   637.9  1993.4   745.8 2031.79
   755.6 2036.97   768.7  2039.3   791.6 2050.29     880 2083.96   984.6 2114.64
#Mann= 5 ,-1 , 0
       0      .1       0     380     .04       0     480      .1       0
   539.7    .045       0   565.9      .1       0
#XS Ineff= 2 , 0
          474.37  1962.5
Permanent Ineff=
       F       F
Bank Sta=539.7,565.9
XS Rating Curve= 0 ,0
Exp/Cntr=0.3,0.1

Type RM Length L Ch R = 1 ,18491   ,345.3,350,350.3
XS GIS Cut Line= 3
     2078776.263      206934.345     2078330.634      206973.957
      2077838.34      207050.097
#Sta/Elev= 30
       0 2077.07    55.5 2053.26    68.6  2050.9   114.3  2036.8   143.7 2025.18
   284.1 1980.37   352.7 1965.14   382.1 1956.33   391.9 1951.36   408.2 1950.26
   431.1  1934.7  436.94 1932.69   450.7  1931.7  455.581932.689   463.8 1935.04
     490 1932.82   506.4  1933.7   519.5 1939.07   542.4 1952.89   552.3 1956.26
   676.8 1986.92     703 1989.09     726 1995.83   742.3 2006.42   771.8 2021.34
     857 2071.97   889.8  2093.9   906.2 2098.63   925.9 2108.99   945.5 2115.98
#Mann= 5 ,-1 , 0
       0      .1       0     350     .04       0  436.94    .045       0
  455.58     .04       0  457.39      .1       0
#XS Ineff= 2 , 0
                           465.6         1938.86
Permanent Ineff=
       F       F
Bank Sta=436.94,455.58
XS Rating Curve= 0 ,0
Exp/Cntr=0.3,0.1

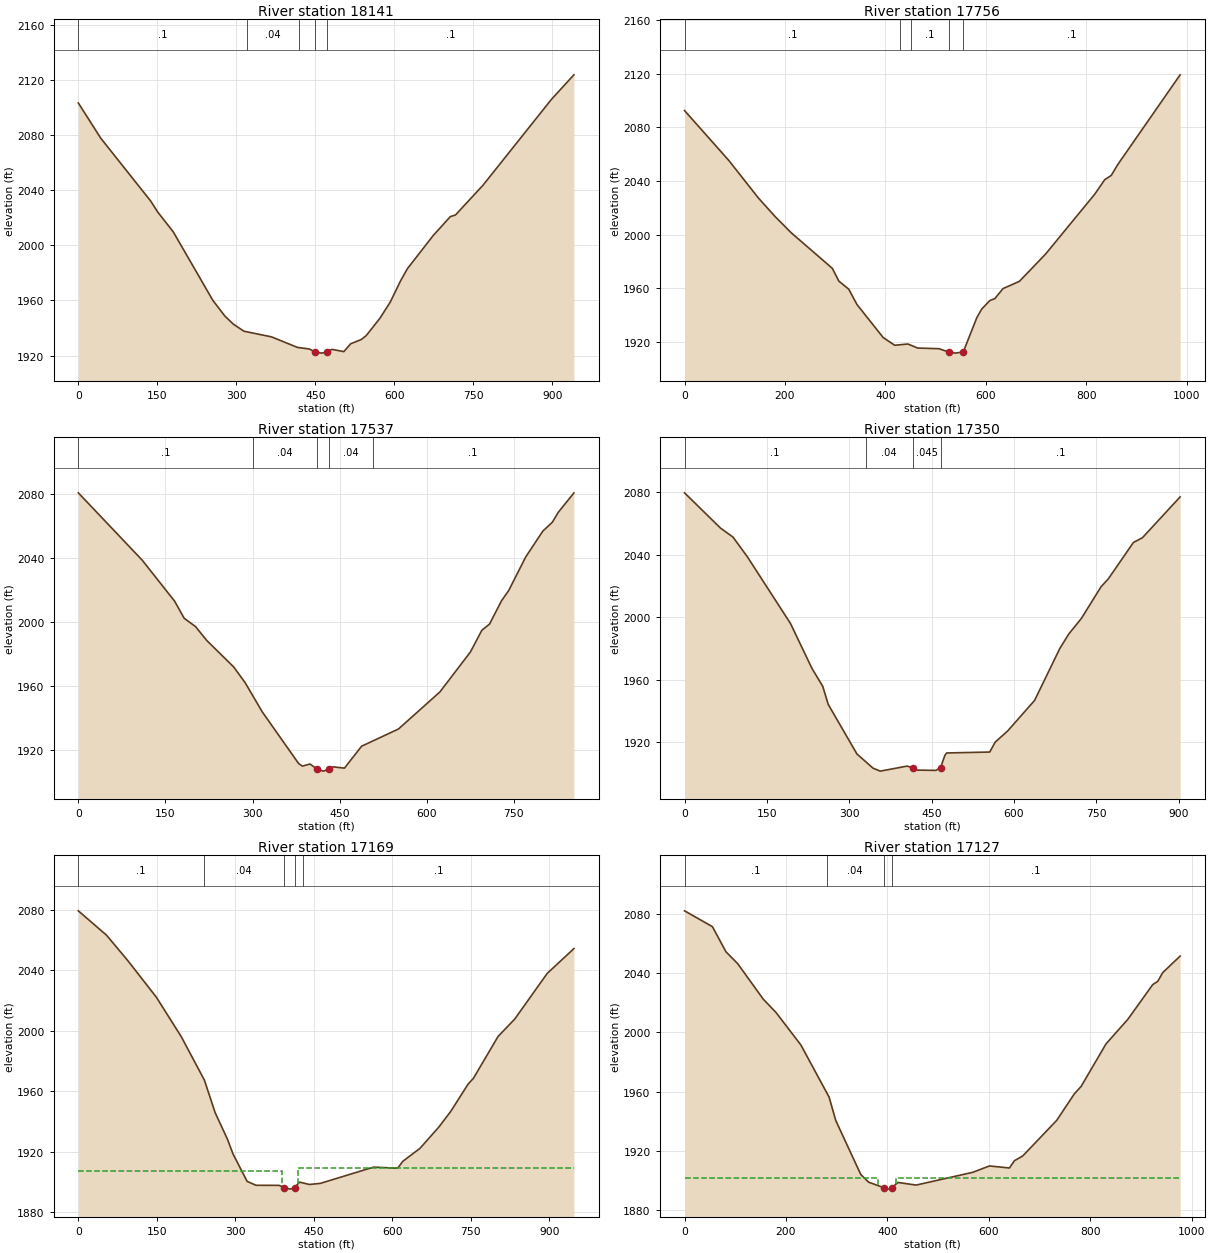
Type RM Length L Ch R = 1 ,18141   ,344.3,385,369.3
XS GIS Cut Line= 3
     2078745.326      206722.557     2078290.177      206666.424
     2077807.919      206681.935
#Sta/Elev= 30
       0 2103.27    42.6 2077.71   137.6 2032.02   150.7 2024.17   180.2 2009.78
   255.5 1960.01   278.4 1948.58   294.8 1942.64   314.5 1937.64   366.9 1933.53
     416  1925.9   438.9 1924.72  449.571922.459   461.9 1921.73   471.6 1922.46
   481.4 1924.47   504.2 1922.84   517.3 1928.55   536.8  1931.5   546.6 1934.39
   572.7 1947.01   592.3 1958.73   611.8 1974.08   624.9    1983   673.8 2007.02
   706.4 2020.79   716.2 2021.98   768.3  2043.5   898.7    2106   941.1 2123.69
#Mann= 5 ,-1 , 0
       0      .1       0     320     .04       0     420      .1       0
  449.57    .045       0   471.6      .1       0
Bank Sta=449.57,471.6
XS Rating Curve= 0 ,0
Exp/Cntr=0.3,0.1

Type RM Length L Ch R = 1 ,17756   ,204.8,218.6,217
XS GIS Cut Line= 3
     2078747.287      206342.032     2078203.019      206416.378
       2077765.4      206417.845
#Sta/Elev= 30
       0 2092.51    88.3 2055.28   147.1 2027.37   179.8 2013.76   212.5 2001.44
   294.3 1974.96   307.4 1965.42     327 1959.43   343.3 1948.06   395.6  1923.4
   418.5 1917.64   444.7 1918.58   464.3 1915.57   506.8 1915.08  525.861912.606
   539.5 1911.78  553.781912.605   555.8 1913.34     582 1938.15   591.8  1944.6
   608.1 1951.01   617.9 1952.38   634.2 1959.86   666.9 1965.27   719.2 1985.67
   817.1  2030.3   836.7 2040.97   849.8  2044.2   862.8 2052.31   986.9 2119.13
#Mann= 5 ,-1 , 0
       0      .1       0     430     .04       0     450      .1       0
  525.86    .045       0  553.78      .1       0
Bank Sta=525.86,553.78
XS Rating Curve= 0 ,0
Exp/Cntr=0.3,0.1

Type RM Length L Ch R = 1 ,17537   ,183.6,187.4,186.7
XS GIS Cut Line= 4
2078728.68386948206255.8693089132078422.35157075206243.737336686
2078067.49138311206222.5063852892077876.41282053206219.473392232
#Sta/Elev= 30
       0 2080.82     110  2038.7   165.8 2013.06   182.2 2002.39   201.9 1997.14
     221 1988.52   267.6 1971.89   287.3 1962.02   316.8 1943.76   379.3 1911.51
   385.8 1909.91     399 1911.22   411.4 1907.91     422 1906.77   431.4    1908
   438.4 1909.46   458.2 1908.64   487.7 1922.35   551.2 1933.12   622.5 1956.29
   675.1 1981.32   694.7 1994.86   707.9 1998.72   728.7 2013.38   740.7 2019.55
   770.2  2040.7   799.7 2056.88   816.1 2062.44   826.4  2068.7   853.2 2080.75
#Mann= 5 ,-1 , 0
       0      .1       0     300     .04       0   411.4    .045       0
   431.4     .04       0  506.57      .1       0
Bank Sta=411.4,431.4
XS Rating Curve= 0 ,0
Exp/Cntr(USF)=0,0
Exp/Cntr=0.3,0.1

Type RM Length L Ch R = 1 ,17350   ,148,180.8,198
XS GIS Cut Line= 2
     2078749.506      206085.597     2077848.465      206030.041
#Sta/Elev= 30
       0 2079.71    65.4 2057.18    88.3 2051.36   114.5 2038.76     193 1996.08
   232.2 1967.28   251.8 1955.86   261.7 1944.31     314 1912.58   343.4 1903.45
   356.5 1901.56   405.6 1904.78   415.4 1903.69   421.9 1902.22   457.9 1902.03
  466.47 1903.88   474.3 1911.66   477.5 1913.19     556 1913.78   565.9 1920.12
   588.8 1927.33   637.8 1946.88   683.6 1980.03     700 1989.36   722.9 1999.29
   758.8  2019.6   771.9 2024.58   817.7 2047.92   834.1 2050.95   902.8 2077.11
#Mann= 4 ,-1 , 0
       0      .1       0     330     .04       0   415.4    .045       0
  466.47      .1       0
Bank Sta=415.4,466.47
XS Rating Curve= 0 ,0
Exp/Cntr=0.5,0.3

Type RM Length L Ch R = 1 ,17169   ,44,42.4,39.9
XS GIS Cut Line= 4
2078756.22145331206060.4196675222078408.83217743 205966.53067404
2078377.14464213205891.4194792552077872.49130217205917.238952462
#Sta/Elev= 30
       0 2079.15      54 2063.02    94.8 2046.17   149.1 2022.11   196.7 1996.04
   240.9 1967.33   261.3 1945.94   285.1  1928.2   295.3 1918.78   322.5 1900.49
   339.5 1897.94   383.5 1897.89  393.311896.403   404.9  1895.4  413.031896.403
   422.7 1900.03   441.4 1898.47   462.5 1899.21     564 1909.93     610  1909.2
   619.9 1913.78   652.6 1922.31   688.9 1936.46   711.8 1946.91   744.7 1964.81
   754.6 1968.48   801.8 1996.18   833.9 2007.79   895.8 2037.87   946.7  2054.2
#Mann= 5 ,-1 , 0
       0      .1       0     240     .04       0  393.31    .045       0
  413.03     .04       0  429.85      .1       0
#XS Ineff= 2 , 0
          388.25  1907.4  419.77         1909.05
Permanent Ineff=
       F       F
Bank Sta=393.31,413.03
XS Rating Curve= 0 ,0
Exp/Cntr(USF)=0,0
Exp/Cntr=0.5,0.3

Type RM Length L Ch R = 1 ,17127   ,72.9,61.6,43.4
XS GIS Cut Line= 4
2078805.51317489205946.5792629252078456.95028659205952.447325018
2078404.13772776205867.9472308852077876.01213942205898.461153766
#Sta/Elev= 30
       0 2081.95      55 2071.28    81.7 2054.35   104.7  2046.4   155.1 2022.49
   180.2 2013.52   229.4 1991.56   285.1 1956.39   298.3 1940.56   347.5 1904.28
   362.9 1899.07  392.441895.413   402.2 1894.37  409.071895.413   420.8 1898.87
   456.7  1897.1   568.4  1905.7   601.3 1909.99   640.7 1908.62   650.6 1913.53
     667 1916.75     734 1940.74   768.9 1958.68     782 1963.55   831.3 1992.33
   874.1 2008.77   923.2 2032.18   933.2 2034.44   943.1 2040.35   977.3 2051.44
#Mann= 4 ,-1 , 0
       0      .1       0     280     .04       0  392.44    .045       0
  409.07      .1       0
#XS Ineff= 2 , 0
          381.87 1901.65  417.91         1901.57
Permanent Ineff=
       F       F
Bank Sta=392.44,409.07
XS Rating Curve= 0 ,0
Exp/Cntr(USF)=0,0
Exp/Cntr=0.5,0.3

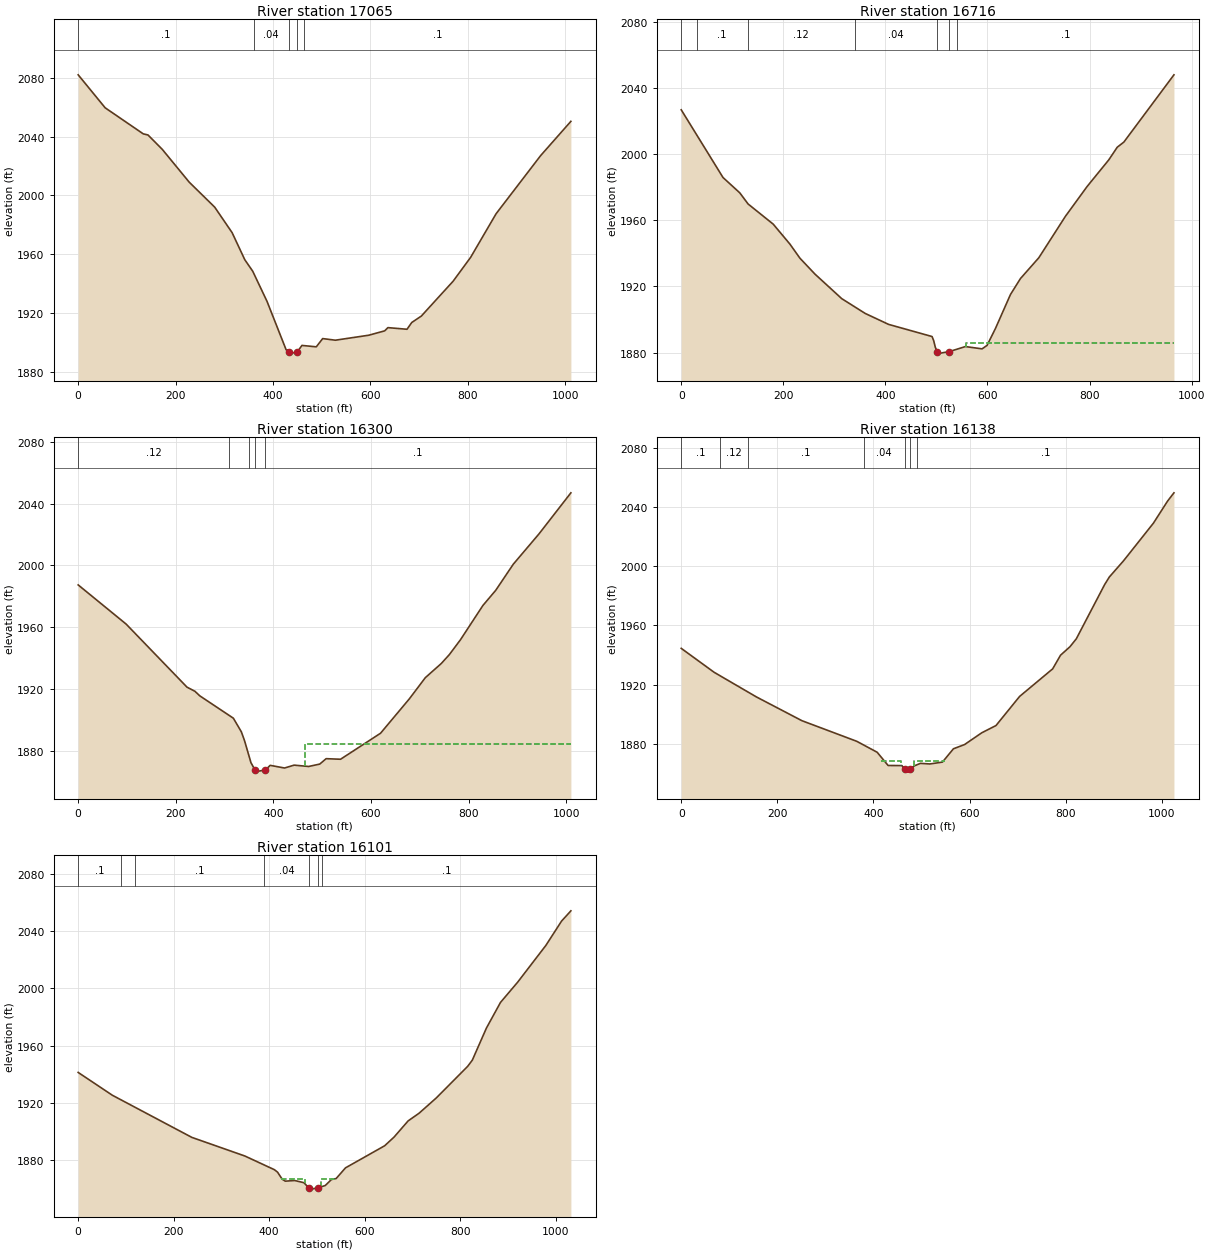
Type RM Length L Ch R = 1 ,17065   ,349.1,348.9,345.1
XS GIS Cut Line= 3
     2078883.597      205809.904     2078452.417      205852.371
     2077875.261      205885.863
#Sta/Elev= 30
       0 2082.05    55.4  2059.6   133.6 2041.86   143.3 2041.11   172.6 2031.32
     228 2008.95   280.2 1991.99     316  1974.6     342 1956.18   358.3 1948.35
   387.7 1927.78   426.8 1894.92  431.991893.525   439.8 1892.58   449.81893.524
   459.4 1897.82   488.8 1896.87   501.9 1902.48     528 1901.38   596.6 1904.78
   629.2 1907.75   635.8 1909.94     675 1908.83   684.8 1913.45   704.4 1917.81
   769.7 1941.56   805.6 1957.79   857.9 1987.49   949.3 2027.06  1011.4 2050.39
#Mann= 5 ,-1 , 0
       0      .1       0     360     .04       0  431.99    .045       0
   449.8     .04       0  463.27      .1       0
Bank Sta=431.99,449.8
XS Rating Curve= 0 ,0
Exp/Cntr=0.3,0.1

Type RM Length L Ch R = 1 ,16716   ,420.2,416.6,408.1
XS GIS Cut Line= 3
      2078747.82      205446.943     2078259.303      205596.862
     2077821.112      205716.612
#Sta/Elev= 30
       0 2026.77    81.9 1985.82   114.6 1976.61     131 1969.83   180.2 1957.65
   212.9 1945.59   232.6 1937.04     262 1927.44   314.5 1912.59   360.3 1903.68
   406.2 1897.04   491.4 1889.69   494.6 1887.24   497.9 1883.07  501.791880.519
   507.7 1879.66   524.5 1880.52   556.8 1883.63   589.4 1882.24   599.2 1884.35
   615.6 1894.55     645 1915.08   664.6 1924.74   700.6 1937.33   752.8 1962.42
   795.3 1980.44   837.8 1996.56   854.2 2004.13   867.2 2007.26   965.3 2047.91
#Mann= 7 ,-1 , 0
       0     .12       0      30      .1       0     130     .12       0
     340     .04       0  501.79    .045       0   524.5     .04       0
     541      .1       0
#XS Ineff= 2 , 0
                          557.12          1885.8
Permanent Ineff=
       F       F
Bank Sta=501.79,524.5
XS Rating Curve= 0 ,0
Exp/Cntr=0.3,0.1

Type RM Length L Ch R = 1 ,16300   ,177.8,161.4,147.7
XS GIS Cut Line= 2
     2078565.479      205005.736     2077775.548      205634.208
#Sta/Elev= 30
       0 1987.35    98.3 1961.98   222.9 1921.18   239.2  1918.5   249.1 1915.56
   317.9 1901.08   334.3 1892.26   340.8 1886.55     354 1872.26  362.191867.619
   370.4 1866.82  383.641867.617   393.3 1870.56   422.8 1868.84   442.4  1870.7
     472 1869.82   494.9 1871.38     508 1874.88   537.5 1874.51   619.4 1891.33
   678.4 1913.58   711.2 1927.31     744 1936.51   760.4 1942.24   783.3 1951.91
   829.2 1974.06   855.4 1983.84   891.4 2000.76   943.9 2020.31  1009.4 2046.95
#Mann= 5 ,-1 , 0
       0     .12       0     310     .04       0     350      .1       0
  362.19    .045       0  383.64      .1       0
#XS Ineff= 2 , 0
                          464.45         1884.17
Permanent Ineff=
       F       F
Bank Sta=362.19,383.64
XS Rating Curve= 0 ,0
Exp/Cntr=0.5,0.3

Type RM Length L Ch R = 1 ,16138   ,36.8,36.8,36.4
XS GIS Cut Line= 4
     2078434.359      204878.537     2078109.923       205161.74
     2078120.774      205224.674      2077747.51      205602.278
#Sta/Elev= 30
       0 1944.56    68.5 1928.37   156.6  1911.7   251.2 1895.66   365.4 1881.72
   407.8 1874.33   430.6 1865.37   459.4 1865.32  464.811862.771   472.2 1861.57
  477.141862.772   484.9 1865.08   497.8 1866.82   517.5 1866.41   543.7 1867.67
   566.6 1876.69   589.6  1879.5   625.6  1887.5   655.1 1892.37   704.3 1912.06
   773.1  1930.7   789.5 1939.93   809.2 1945.69   822.3    1951   881.3 1987.67
   891.1  1992.8   920.6 2003.73   982.9 2029.22  1012.4 2044.16  1025.5 2049.67
#Mann= 7 ,-1 , 0
       0      .1       0      80     .12       0     140      .1       0
     380     .04       0  464.81    .045       0  477.14     .04       0
  490.65      .1       0
#XS Ineff= 2 ,-1
  416.44  458.341868.504  485.08  549.81 1868.29
Permanent Ineff=
       F       F
Bank Sta=464.81,477.14
XS Rating Curve= 0 ,0
Exp/Cntr=0.5,0.3

Type RM Length L Ch R = 1 ,16101   ,94.4,101.8,110.4
XS GIS Cut Line= 4
     2078420.253      204868.771     2078075.201       205172.59
     2078086.052      205235.524     2077729.064      205596.853
#Sta/Elev= 30
       0 1941.35   71.421925.473     238 1896.06   348.9 1883.09   410.8 1873.54
   417.4 1871.82   427.1 1866.92   433.7 1865.54   453.2 1865.99   472.5 1864.49
  482.611860.956   488.5 1859.99  502.281860.957   517.2 1862.49   530.2 1866.69
     540 1867.36   559.7 1874.83   641.6 1890.22   661.2 1896.24   690.7 1907.54
   713.7 1912.92   749.7 1923.56   815.3 1945.56   825.1 1949.89   854.6 1972.24
   884.1 1990.16   920.1  2004.3   979.1 2029.91  1011.9 2046.84  1031.5 2054.03
#Mann= 7 ,-1 , 0
       0      .1       0      90     .12       0     120      .1       0
     390     .04       0  482.61    .045       0  502.28     .04       0
  509.75      .1       0
#XS Ineff= 2 ,-1
  424.92  474.09 1866.75  508.67  540.85 1867.02
Permanent Ineff=
       F       F
Bank Sta=482.61,502.28
XS Rating Curve= 0 ,0
Exp/Cntr=0.5,0.3