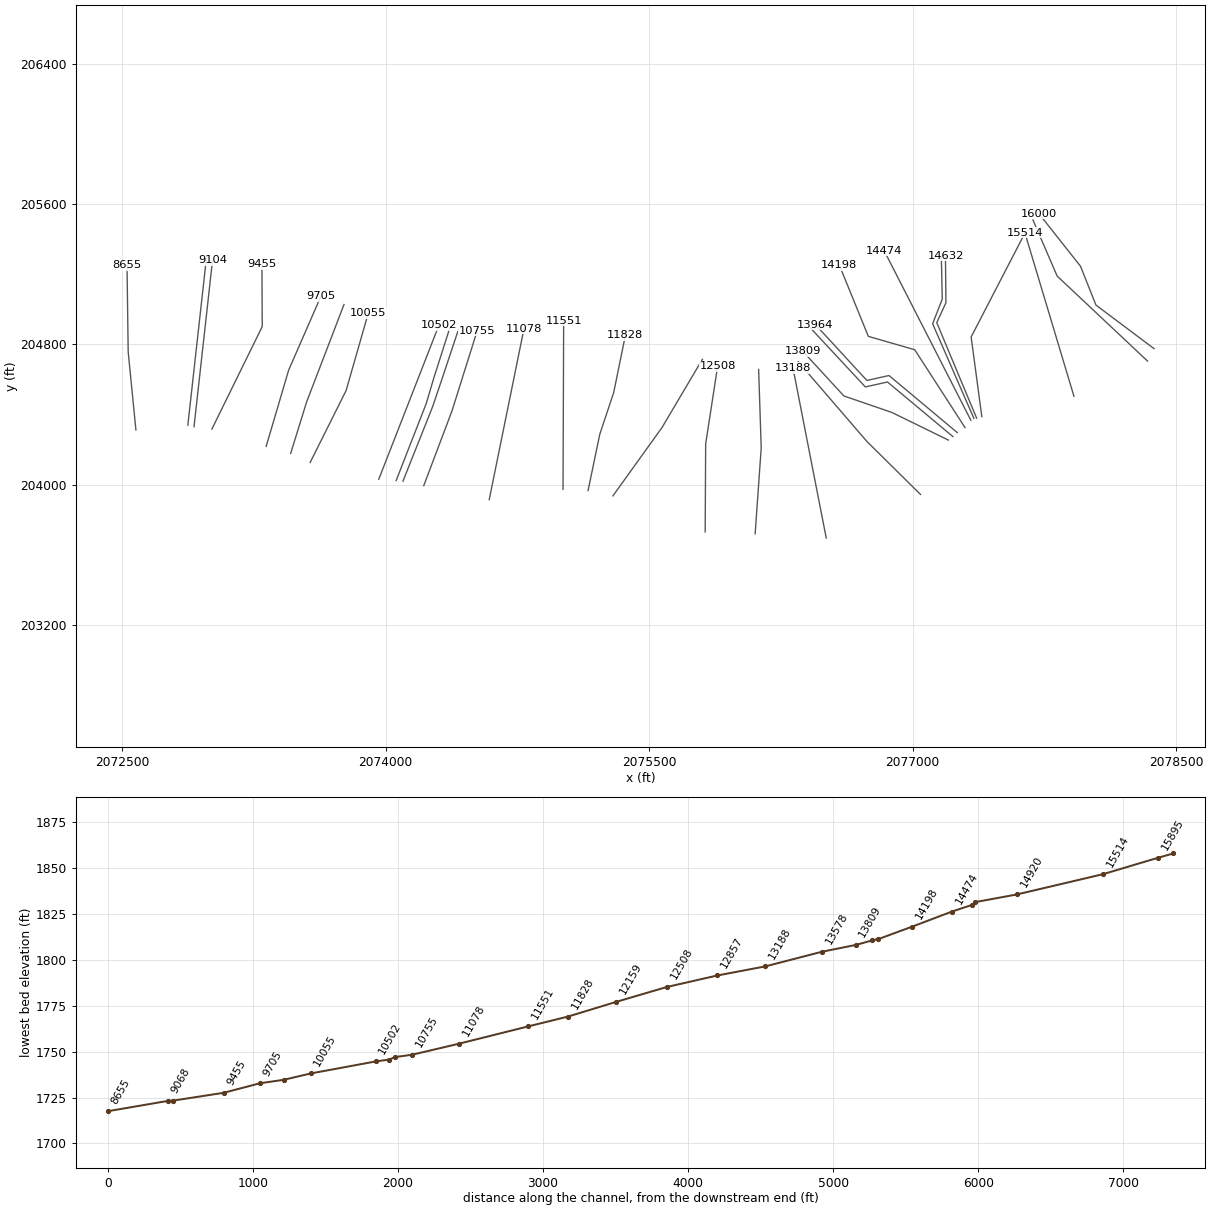
HEC-RAS study LAURELCK1.prj: LAURELCK1

--- LAURELCK1.g01 (geometry) --- (continued)

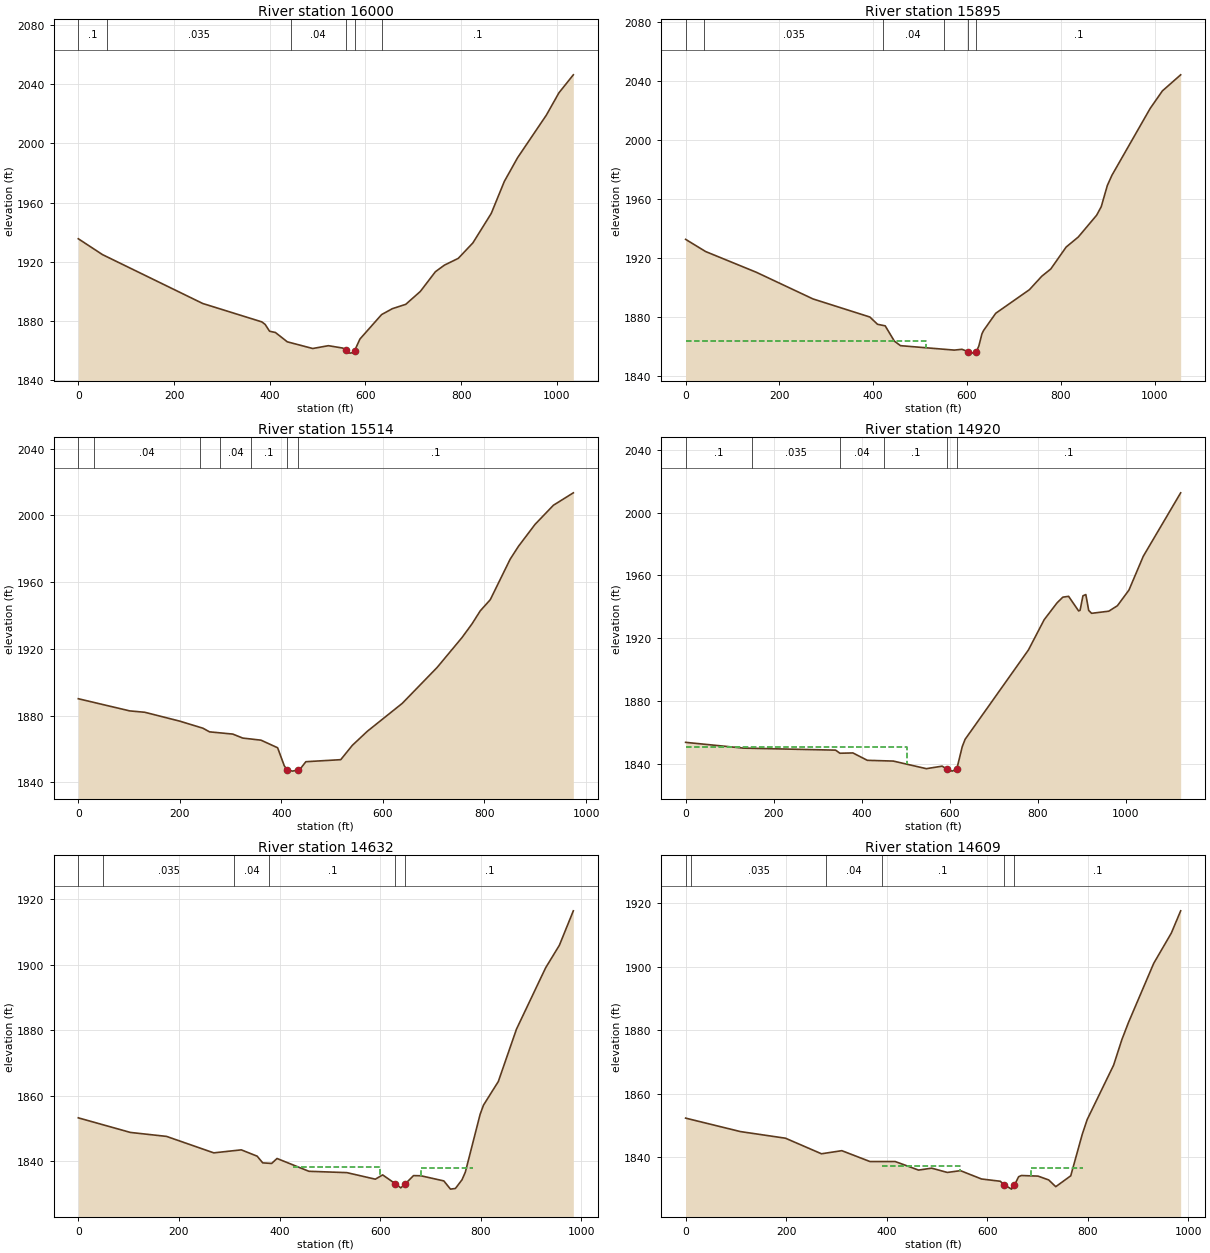
Type RM Length L Ch R = 1 ,16000   ,98.5,105.1,110.8
XS GIS Cut Line= 4
2078373.82368184204775.7686972232078043.22743866205024.474127876
2077955.27064001205245.8826210182077718.69718158205546.148933636
#Sta/Elev= 30
       0 1935.47    50.6 1924.72     260 1891.61   383.4 1879.16   390.4 1877.43
   399.6 1872.83   411.9 1871.95   436.6 1865.66   489.8 1861.12   522.5 1863.03
   552.8  1861.4   558.81859.791   567.2 1857.99   574.3 1858.33   577.3  1859.7
   588.4 1867.54   633.6 1884.09   656.1  1888.1   684.1 1891.05   714.5 1899.76
   746.1 1913.16   764.7 1917.56   793.8 1922.19   824.3 1932.64   862.7 1952.62
     890 1974.27   917.7 1990.36   977.8  2019.2  1004.1 2034.33  1034.2 2046.52
#Mann= 6 ,-1 , 0
       0      .1       0      60    .035       0   443.7     .04       0
   558.8    .045       0   577.3     .04       0   633.7      .1       0
Bank Sta=558.8,577.3
XS Rating Curve= 0 ,0
Exp/Cntr(USF)=0,0
Exp/Cntr=0.3,0.1

Type RM Length L Ch R = 1 ,15895   ,385.7,380.5,367.1
XS GIS Cut Line= 3
     2078336.703      204704.925      2077822.38      205189.951
     2077684.576      205510.047
#Sta/Elev= 30
       0 1932.68    42.6 1924.43   150.6 1910.41   271.6 1892.33   392.8 1880.09
   409.1 1875.17   425.5 1874.11   445.1 1863.73   458.2 1860.69   572.8 1857.69
   589.1 1858.23   601.71856.739     612 1855.64  619.941856.739   625.1 1860.42
   631.7 1868.66     635 1870.84   661.1 1882.61     733  1898.6   759.1 1907.64
   778.6 1912.65   811.2 1927.44   837.2 1934.28   876.3 1949.04   886.1 1954.81
   899.1  1969.2   908.9 1976.08   990.3 2021.28  1016.4 2033.18  1055.4 2044.08
#Mann= 6 ,-1 , 0
       0      .1       0      40    .035       0     420     .04       0
     550      .1       0   601.7    .045       0  619.94      .1       0
#XS Ineff= 2 , 0
          513.13 1863.61
Permanent Ineff=
       F       F
Bank Sta=601.7,619.94
XS Rating Curve= 0 ,0
Exp/Cntr=0.3,0.1

Type RM Length L Ch R = 1 ,15514   ,604,593.7,580.3
XS GIS Cut Line= 2
     2077917.909      204503.999     2077638.395      205438.027
#Sta/Elev= 30
       0 1890.08   101.4 1882.78   130.9 1881.96   199.6 1876.66   245.4 1872.41
   258.5 1870.22   304.3 1868.88   323.9 1866.49   359.9 1865.23   392.6 1860.68
   405.7 1849.87  411.211847.432     422 1846.67  433.411847.431   438.4  1848.5
   448.2 1852.32   516.9 1853.54   539.8 1862.15   569.3 1870.57     638 1887.29
   706.7 1908.82   755.8 1926.78   775.4 1934.95   791.7 1942.78   811.4 1949.46
   850.6 1973.76     867  1981.5   899.7 1994.66   935.7 2006.08     975 2013.54
#Mann= 7 ,-1 , 0
       0      .1       0      30     .04       0     240     .06       0
     280     .04       0     340      .1       0  411.21    .045       0
  433.41      .1       0
Bank Sta=411.21,433.41
XS Rating Curve= 0 ,0
Exp/Cntr=0.3,0.1

Type RM Length L Ch R = 1 ,14920   ,280.6,288.7,283
XS GIS Cut Line= 3
     2077393.604       204387.68      2077332.84      204842.541
     2077638.395      205434.555
#Sta/Elev= 30
       0 1853.92   131.1 1850.26   340.9 1848.97   350.7    1847   380.2 1847.19
     413  1842.5     472 1842.02   547.1 1837.19     583 1838.79  593.771836.965
   605.9 1835.63  616.291836.967   628.7 1851.19   635.2 1855.84     779 1912.58
   814.9 1931.87   844.3 1942.63   857.3  1946.2   870.4 1946.74   893.2 1937.45
   896.5 1937.83     903 1947.08   909.6 1947.86   916.1 1937.77   922.6 1935.93
   961.8 1937.29   981.4 1940.78  1007.6 1950.73  1040.2 1972.23  1125.1 2012.52
#Mann= 6 ,-1 , 0
       0      .1       0     150    .035       0     350     .04       0
     450      .1       0  593.77    .045       0  616.29      .1       0
#XS Ineff= 2 , 0
          502.01 1850.77
Permanent Ineff=
       F       F
Bank Sta=593.77,616.29
XS Rating Curve= 0 ,0
Exp/Cntr=0.5,0.3

Type RM Length L Ch R = 1 ,14632   ,24.4,22.4,24.7
XS GIS Cut Line= 4
 2077364.0369539204379.2586748552077137.13855299204924.336442567
2077189.29910492205037.7856430242077186.69107732205306.412485485
#Sta/Elev= 30
       0 1853.21   103.6 1848.75   175.4 1847.54   269.3 1842.51   323.9 1843.43
   355.5  1841.5   366.6 1839.45   384.3 1839.28     395 1840.79   458.4 1836.88
   533.7 1836.47   590.4 1834.47   604.9 1835.78   630.2 1833.07     641 1831.82
   650.2 1833.09   666.3 1835.56     681 1835.51   726.5 1833.94   739.7 1831.43
   749.5 1831.63   762.6 1834.28   769.2 1836.59   798.7 1854.31   805.3 1857.08
   834.8 1864.31   870.9 1880.31   928.8 1899.04   956.2 1905.95   983.9 1916.46
#Mann= 6 ,-1 , 0
       0      .1       0      50    .035       0     310     .04       0
     380      .1       0   630.2    .045       0   650.2      .1       0
#XS Ineff= 4 ,-1
     427   600.41838.091  603.67   625.81833.047  653.15  674.071833.113
  681.14  784.531837.831
Permanent Ineff=
       F       F       F       F
Bank Sta=630.2,650.2
XS Rating Curve= 0 ,0
Exp/Cntr(USF)=0,0
Exp/Cntr=0.5,0.3

Type RM Length L Ch R = 1 ,14609   ,118.1,135.5,148.2
XS GIS Cut Line= 4
2077348.38878832204377.9546610562077113.66630462204917.816373575
2077168.43488415205058.6498637972077163.21882895205303.804457888
#Sta/Elev= 30
       0 1852.27   109.3 1848.02   198.7 1845.94   270.3 1841.03   310.8 1842.01
   366.9 1838.58     417 1838.59   463.5 1835.89   489.5  1836.5   520.7 1835.15
   546.9 1835.71   588.7 1833.09   626.1 1832.37   634.4 1831.22   648.5 1829.89
     654 1831.07   662.6  1833.8   668.1 1834.18   701.3 1833.99   722.4 1832.79
   736.5 1830.66   766.3 1834.09   789.3 1847.23   799.1 1851.86   851.6 1868.97
     868 1877.01   881.1 1882.39   931.4 1901.06   966.5 1910.62     985 1917.61
#Mann= 6 ,-1 , 0
       0      .1       0      10    .035       0     280     .04       0
     390      .1       0   634.4    .045       0     654      .1       0
#XS Ineff= 4 ,-1
  391.12  545.85 1837.22  604.62  628.23 1831.26  660.33  674.96 1831.43
  686.76  789.68 1836.44
Permanent Ineff=
       F       F       F       F
Bank Sta=634.4,654
XS Rating Curve= 0 ,0
Exp/Cntr(USF)=0,0
Exp/Cntr=0.5,0.3

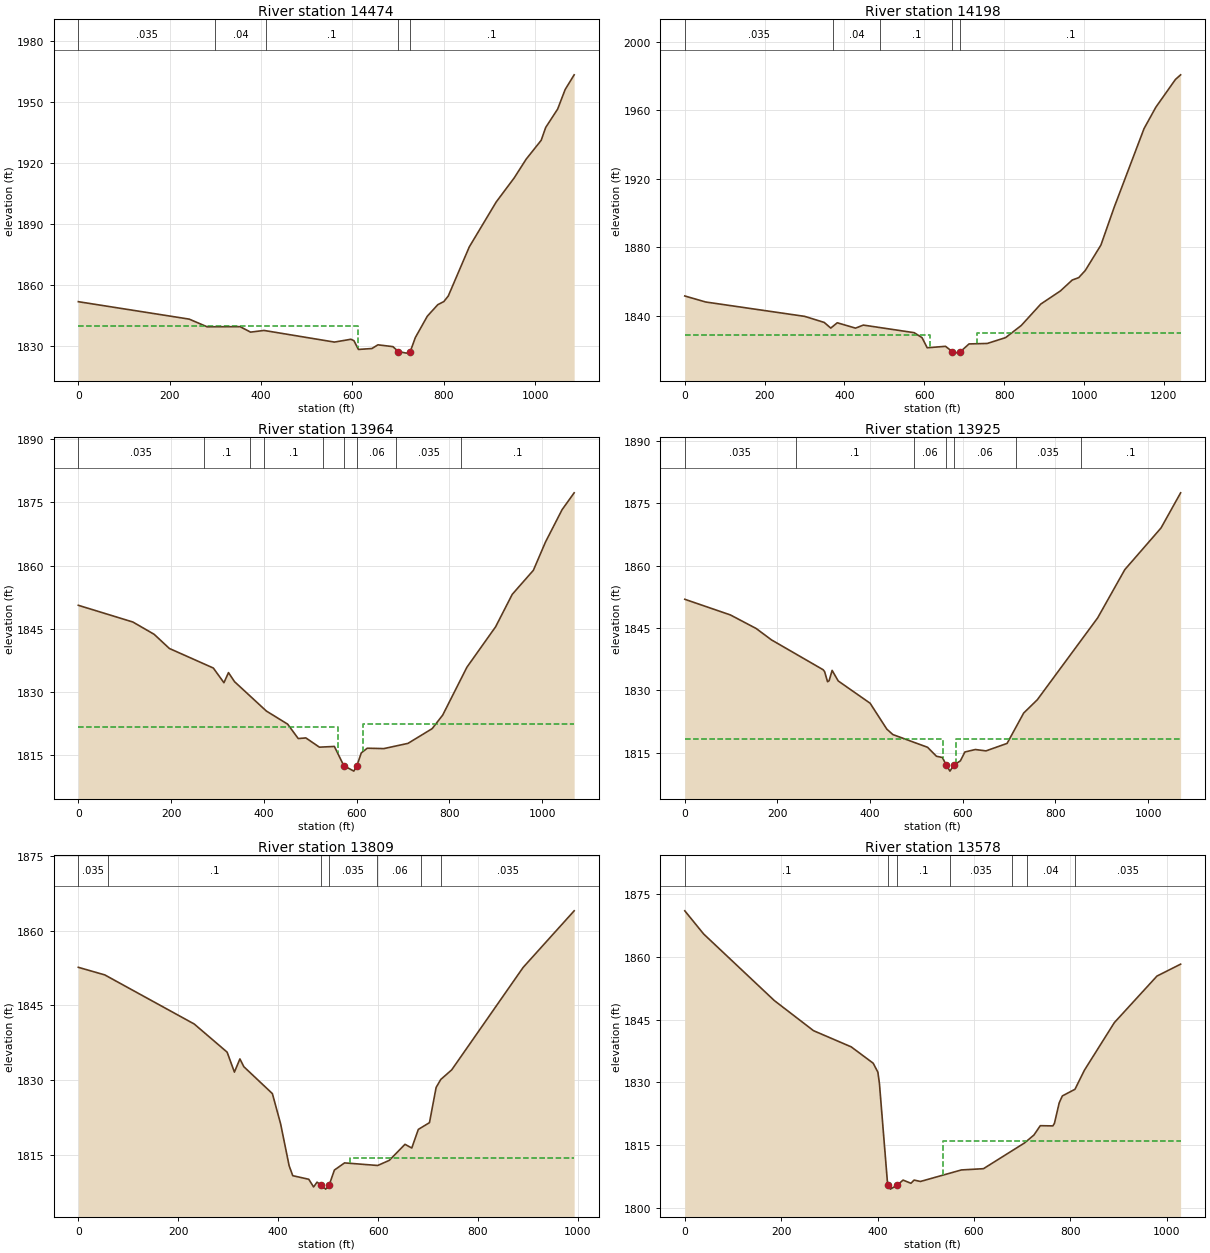
Type RM Length L Ch R = 1 ,14474   ,259.8,276.2,287
XS GIS Cut Line= 2
     2077331.021      204367.423     2076837.965      205334.437
#Sta/Elev= 30
       0 1851.66   242.7 1843.08     282 1839.29   354.2 1839.36   377.1 1836.67
   406.6  1837.5   560.8 1831.77   596.8 1833.16   603.4 1832.45   613.2 1828.14
   642.8  1828.6   655.9 1830.42   688.7 1829.53  700.591827.105   718.2 1826.33
   726.71827.105   737.8    1834   764.1 1844.54     787  1850.2   800.2 1851.72
     810  1854.5   855.9 1878.64   914.9 1900.78   954.3 1912.64   980.5 1921.87
  1013.3 1931.13  1023.2 1937.46  1049.4 1946.54  1065.8 1956.14  1085.5 1963.38
#Mann= 5 ,-1 , 0
       0    .035       0     300     .04       0     410      .1       0
  700.59    .045       0   726.7      .1       0
#XS Ineff= 2 , 0
          611.83  1839.7
Permanent Ineff=
       F       F
Bank Sta=700.59,726.7
XS Rating Curve= 0 ,0
Exp/Cntr=0.3,0.1

Type RM Length L Ch R = 1 ,14198   ,208.6,233.8,239.5
XS GIS Cut Line= 4
     2077298.118       204325.18     2077011.659      204769.624
      2076747.77      204846.013      2076582.84      205252.263
#Sta/Elev= 30
       0 1851.43    52.2 1847.92   300.3 1839.52   349.2 1835.99   365.6 1832.68
   381.9 1835.78   427.6 1832.65   447.2 1834.43   574.6 1829.99   594.2  1827.1
   607.2 1821.18     653 1822.02  670.431818.877   675.9 1818.05  690.231818.878
   711.9 1823.42   757.7  1823.7   803.5 1827.11   842.8 1834.21   891.8 1846.74
   940.9 1854.39   970.4 1860.74   986.7 1862.16  1003.1 1866.33  1042.3 1881.19
  1075.1    1903  1150.3 1949.21  1179.8 1961.69  1228.8 1977.88  1241.9 1980.61
#Mann= 5 ,-1 , 0
       0    .035       0     370     .04       0     490      .1       0
  670.43    .045       0  690.23      .1       0
#XS Ineff= 2 , 0
          613.63 1828.64  732.73         1829.65
Permanent Ineff=
       F       F
Bank Sta=670.43,690.23
XS Rating Curve= 0 ,0
Exp/Cntr=0.5,0.3

Type RM Length L Ch R = 1 ,13964   ,51.2,38.4,38.8
XS GIS Cut Line= 4
     2077253.803      204296.939     2076865.348       204622.46
      2076739.48      204594.248     2076446.512      204913.259
#Sta/Elev= 30
       0 1850.57   117.7  1846.6   163.5 1843.69   196.2 1840.34     291  1835.7
   313.9 1832.22   323.7 1834.61   336.8 1832.46   405.4  1825.5   451.2  1822.4
   474.1 1818.98   490.5 1819.13   519.7 1816.94     552 1817.11  572.281812.557
   593.9 1811.26  600.511812.556     610 1815.58   622.9 1816.69   658.6  1816.6
   710.7 1817.84   762.8 1821.33   785.6 1824.56   837.7 1835.89   899.6 1845.48
   935.4 1853.16     981 1858.87  1007.1 1865.57  1042.9 1873.24  1068.9 1877.23
#Mann= 9 ,-1 , 0
       0    .035       0     270      .1       0     370     .04       0
     400      .1       0  526.81     .06       0  572.28    .045       0
  600.51     .06       0  685.81    .035       0  825.81      .1       0
#XS Ineff= 2 , 0
          558.74 1821.74  613.75         1822.36
Permanent Ineff=
       F       F
Bank Sta=572.28,600.51
XS Rating Curve= 0 ,0
Exp/Cntr=0.5,0.3

Type RM Length L Ch R = 1 ,13925   ,124.3,116.5,108
XS GIS Cut Line= 4
     2077228.847      204274.153     2076856.668      204585.568
       2076730.8      204557.356      2076420.47      204891.557
#Sta/Elev= 30
       0 1851.91    98.4 1848.15   154.1 1844.89   186.9 1842.17   298.4    1835
   301.7 1834.56   308.2  1832.1   311.5 1832.34     318 1834.83   331.2 1832.29
     400 1826.94   436.1 1820.72   449.2 1819.41     524 1816.36   543.3  1814.2
   556.2  1813.9  564.311812.077   572.4 1810.63  580.781812.078   594.9  1813.1
   604.6 1815.23   627.3 1815.82   650.1 1815.49   695.7 1817.29   731.5 1824.58
   760.9 1827.77   891.2 1847.44   949.8 1859.03    1028 1869.04  1070.3 1877.48
#Mann= 7 ,-1 , 0
       0    .035       0     240      .1       0  495.28     .06       0
  564.31    .045       0  580.78     .06       0  714.27    .035       0
  854.27      .1       0
#XS Ineff= 2 , 0
          558.21 1818.46  585.65         1818.46
Permanent Ineff=
       F       F
Bank Sta=564.31,580.78
XS Rating Curve= 0 ,0
Exp/Cntr=0.5,0.3

Type RM Length L Ch R = 1 ,13809   ,237.3,230.3,222.8
XS GIS Cut Line= 4
2077203.08836194204254.0938914642076881.59109792204411.809530414
2076608.62172282204505.8323151732076375.08125745 204760.60373194
#Sta/Elev= 30
       0 1852.66    52.9 1851.14     232 1841.27   297.8 1835.62   312.4 1831.61
   323.4 1834.26   331.3 1832.69   388.4 1827.29   404.9 1821.21   421.9 1812.81
   429.2  1810.8   461.2 1810.08   470.9 1808.54   477.8  1809.5   486.71808.855
   495.1  1808.1   501.9 1808.87   512.5 1811.93   532.9 1813.37   599.2 1812.85
   622.4 1813.88   653.8  1817.1   667.4 1816.36   680.5  1820.1   702.8 1821.45
   716.1 1828.52   725.4 1830.13   747.3 1832.06   890.3 1852.64   992.4 1864.01
#Mann= 7 ,-1 , 0
       0    .035       0      60      .1       0   486.7    .045       0
   501.9    .035       0   598.1     .06       0  686.81     .04       0
  726.81    .035       0
#XS Ineff= 2 , 0
                           543.1         1814.33
Permanent Ineff=
       F       F
Bank Sta=486.7,501.9
XS Rating Curve= 0 ,0
Exp/Cntr(USF)=0,0
Exp/Cntr=0.3,0.1

Type RM Length L Ch R = 1 ,13578   ,397.7,390.4,375.7
XS GIS Cut Line= 3
     2077044.666      203943.754     2076739.289      204246.593
      2076348.92      204700.999
#Sta/Elev= 30
       0 1871.04    39.1  1865.5   185.7 1849.58   267.2 1842.36   345.4 1838.49
     391 1834.58   400.8 1832.42     404 1829.68   420.3  1806.5  422.161805.406
   426.8 1804.45  440.861805.407     453 1806.61   469.4 1805.85   475.9 1806.62
     489 1806.28   574.1 1809.04   619.9 1809.34   705.1  1815.5   724.7  1817.4
   737.8 1819.63     764 1819.58   767.2  1820.2   777.1 1825.09   783.6 1826.75
   809.8 1828.34   829.4  1832.9   891.6  1844.3     980 1855.43  1029.1 1858.28
#Mann= 7 ,-1 , 0
       0      .1       0  422.16    .045       0  440.86      .1       0
  550.08    .035       0  680.08     .06       0  710.08     .04       0
  810.08    .035       0
#XS Ineff= 2 , 0
                          536.39         1816.07
Permanent Ineff=
       F       F
Bank Sta=422.16,440.86
XS Rating Curve= 0 ,0
Exp/Cntr=0.3,0.1

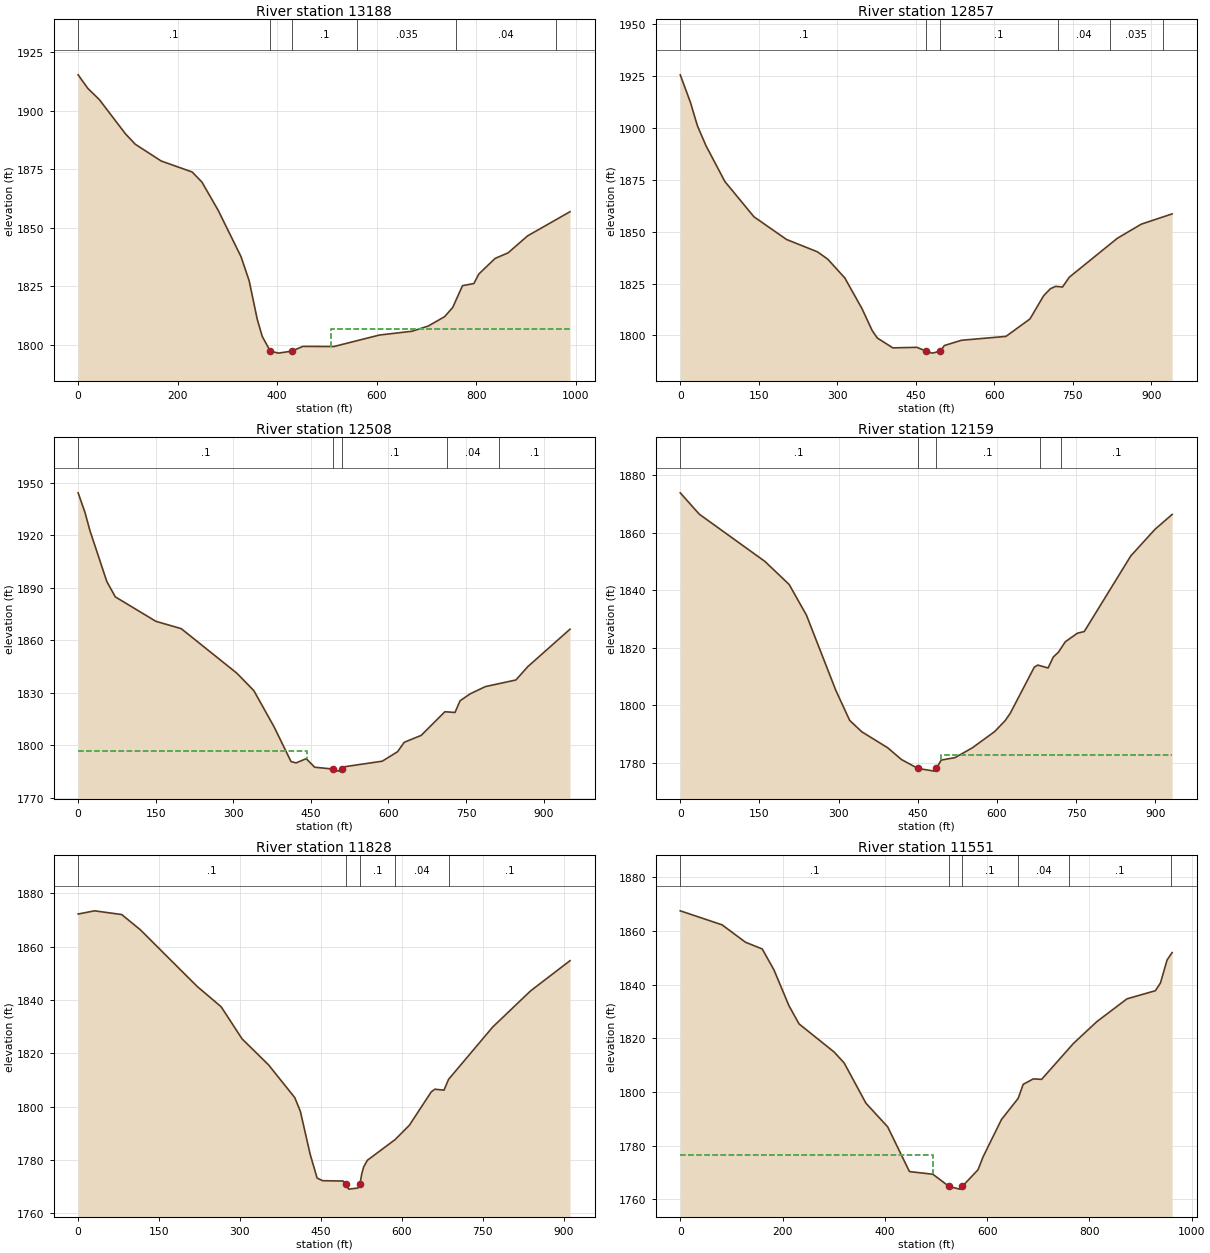
Type RM Length L Ch R = 1 ,13188   ,333.5,331,311.7
XS GIS Cut Line= 2
     2076508.187      203694.972     2076318.951      204665.458
#Sta/Elev= 30
       0 1915.24    19.6 1909.43    42.6 1904.68      95  1890.1   114.6 1885.66
     167 1878.46   229.2 1873.78   248.8 1869.49   281.6 1857.39   327.4 1837.67
   343.8 1827.36   360.2 1810.81     370 1803.68  386.131797.348   402.7 1796.47
  429.621797.349   451.8 1799.34     514 1799.28   605.7 1804.19   671.2 1805.81
   703.9 1808.03   736.7 1812.03     753 1815.96   772.7 1825.27   795.6 1826.16
   805.4 1830.21   838.2 1836.88   864.4 1839.28   903.6 1846.52   988.8 1856.82
#Mann= 6 ,-1 , 0
       0      .1       0  386.13    .045       0  429.62      .1       0
     560    .035       0     760     .04       0     960    .035       0
#XS Ineff= 2 , 0
                          508.17         1806.56
Permanent Ineff=
       F       F
Bank Sta=386.13,429.62
XS Rating Curve= 0 ,0
Exp/Cntr=0.3,0.1

Type RM Length L Ch R = 1 ,12857   ,346.4,348.6,345
XS GIS Cut Line= 3
     2076103.632      203719.235     2076138.152       204209.29
     2076123.484      204657.378
#Sta/Elev= 30
       0 1925.37    19.6 1912.03    32.8 1900.85    49.1 1891.32    85.2 1874.07
   140.8 1857.08   203.1 1846.17     262 1840.24   281.7 1836.73   314.4 1827.65
   347.2 1812.91   366.8 1802.28   376.6 1798.75   406.1 1794.04     452  1794.3
  469.931792.455   481.4 1791.51  496.961792.454   504.4 1795.16   537.1 1797.69
   622.2 1799.56     668 1807.94   694.2 1819.13   707.2 1822.52   717.1 1823.64
   730.2 1823.31   743.2 1828.03   834.9 1846.75   880.7 1853.54   939.6 1858.48
#Mann= 6 ,-1 , 0
       0      .1       0  469.93    .045       0  496.96      .1       0
  721.27     .04       0  821.27    .035       0  921.27     .08       0
Bank Sta=469.93,496.96
XS Rating Curve= 0 ,0
Exp/Cntr=0.3,0.1

Type RM Length L Ch R = 1 ,12508   ,357.4,349.6,343.2
XS GIS Cut Line= 3
     2075819.263      203729.891     2075822.074      204232.933
     2075890.238      204675.538
#Sta/Elev= 30
       0 1944.25    13.1 1933.19    22.9 1922.59    55.5 1893.54    71.9  1884.8
   150.3 1870.83   199.3 1866.65   307.1 1841.13   339.7 1831.22   378.9 1810.49
   411.6 1790.67   421.4 1789.94     441 1792.34   457.3 1787.46  493.431786.398
     503 1785.23  509.981786.397   516.1 1787.78     588 1790.92   617.5 1796.33
   630.5 1801.73   663.2 1805.65     709 1819.16   728.6 1818.76   738.4 1825.44
     758 1829.41   787.4 1833.54   846.3 1837.31   869.2  1844.9   950.9 1866.34
#Mann= 5 ,-1 , 0
       0      .1       0  493.43    .045       0  509.98      .1       0
  713.05     .04       0  813.05      .1       0
#XS Ineff= 2 , 0
          442.06 1796.65
Permanent Ineff=
       F       F
Bank Sta=493.43,509.98
XS Rating Curve= 0 ,0
Exp/Cntr=0.3,0.1

Type RM Length L Ch R = 1 ,12159   ,321.4,331.1,333.6
XS GIS Cut Line= 3
     2075294.242      203935.566      2075574.46      204326.971
     2075803.228      204714.885
#Sta/Elev= 30
       0 1873.94      36 1866.52   160.5 1850.06   206.3 1842.05     239  1831.4
   294.7 1805.21   320.9 1794.78   343.8 1790.81     393 1785.23   419.2 1781.12
  450.391778.031   481.4 1777.11  485.011778.031   494.4 1780.96   520.5 1781.81
   553.2 1785.21   595.6 1790.88   615.2 1794.63     625 1797.21   670.6 1813.28
   677.2 1814.01   696.8    1813   706.6 1816.82   716.3 1818.48   729.4 1822.12
   752.2 1825.09   765.3 1825.68   853.4 1851.99   899.1 1861.22   931.7 1866.42
#Mann= 5 ,-1 , 0
       0      .1       0  450.39    .045       0  485.01      .1       0
  681.37     .04       0  721.37      .1       0
#XS Ineff= 2 , 0
                          494.16         1782.86
Permanent Ineff=
       F       F
Bank Sta=450.39,485.01
XS Rating Curve= 0 ,0
Exp/Cntr=0.3,0.1

Type RM Length L Ch R = 1 ,11828   ,265.8,276.6,280.5
XS GIS Cut Line= 4
2075152.78505558203965.9595510732075219.51090283204287.456815088
 2075298.3687223204524.0302735142075365.09456955204851.593523642
#Sta/Elev= 30
       0  1872.2    30.6  1873.4    80.8 1872.01   115.4 1866.29   220.8 1845.06
   265.2 1837.45     304 1825.42     353  1815.7   401.6 1803.44     412 1798.32
   430.1 1782.28   443.1 1773.27   453.3 1772.29   491.4 1772.16  496.77 1770.91
   501.7 1769.13     519 1769.55   522.5 1770.93   525.9 1774.89   529.4 1777.44
   536.3 1779.94   587.9 1787.72   614.2 1793.07   654.8  1805.6   661.5 1806.57
   678.3  1806.2   686.8 1810.25   768.7 1829.87     839 1843.42     912 1854.72
#Mann= 5 ,-1 , 0
       0      .1       0  496.77    .045       0   522.5      .1       0
  587.72     .04       0  687.72      .1       0
Bank Sta=496.77,522.5
XS Rating Curve= 0 ,0
Exp/Cntr(USF)=0,0
Exp/Cntr=0.3,0.1

Type RM Length L Ch R = 1 ,11551   ,468.5,473.5,464.4
XS GIS Cut Line= 2
     2075010.357      203973.184     2075013.829      204934.989
#Sta/Elev= 30
       0 1867.52    81.8  1862.3   127.6  1855.8   160.3  1853.3   183.2 1845.51
   212.6 1832.13   232.3 1825.35     301 1814.85   320.6 1810.76   363.1 1795.78
   405.7 1786.94   448.2 1770.27     494 1769.28  525.471764.746   546.3 1763.73
  551.481764.747   582.3 1770.97   592.1 1775.75   628.1 1789.69   660.8 1797.59
   670.6 1802.81   690.3 1804.84   706.6 1804.67   768.8 1818.06   814.6  1826.2
   873.5 1834.69   929.1 1837.73   938.9 1840.59     952 1849.22   961.8 1851.94
#Mann= 6 ,-1 , 0
       0      .1       0  525.47    .045       0  551.48      .1       0
     660     .04       0     760      .1       0     960     .05       0
#XS Ineff= 2 , 0
          494.27 1776.42
Permanent Ineff=
       F       F
Bank Sta=525.47,551.48
XS Rating Curve= 0 ,0
Exp/Cntr=0.3,0.1

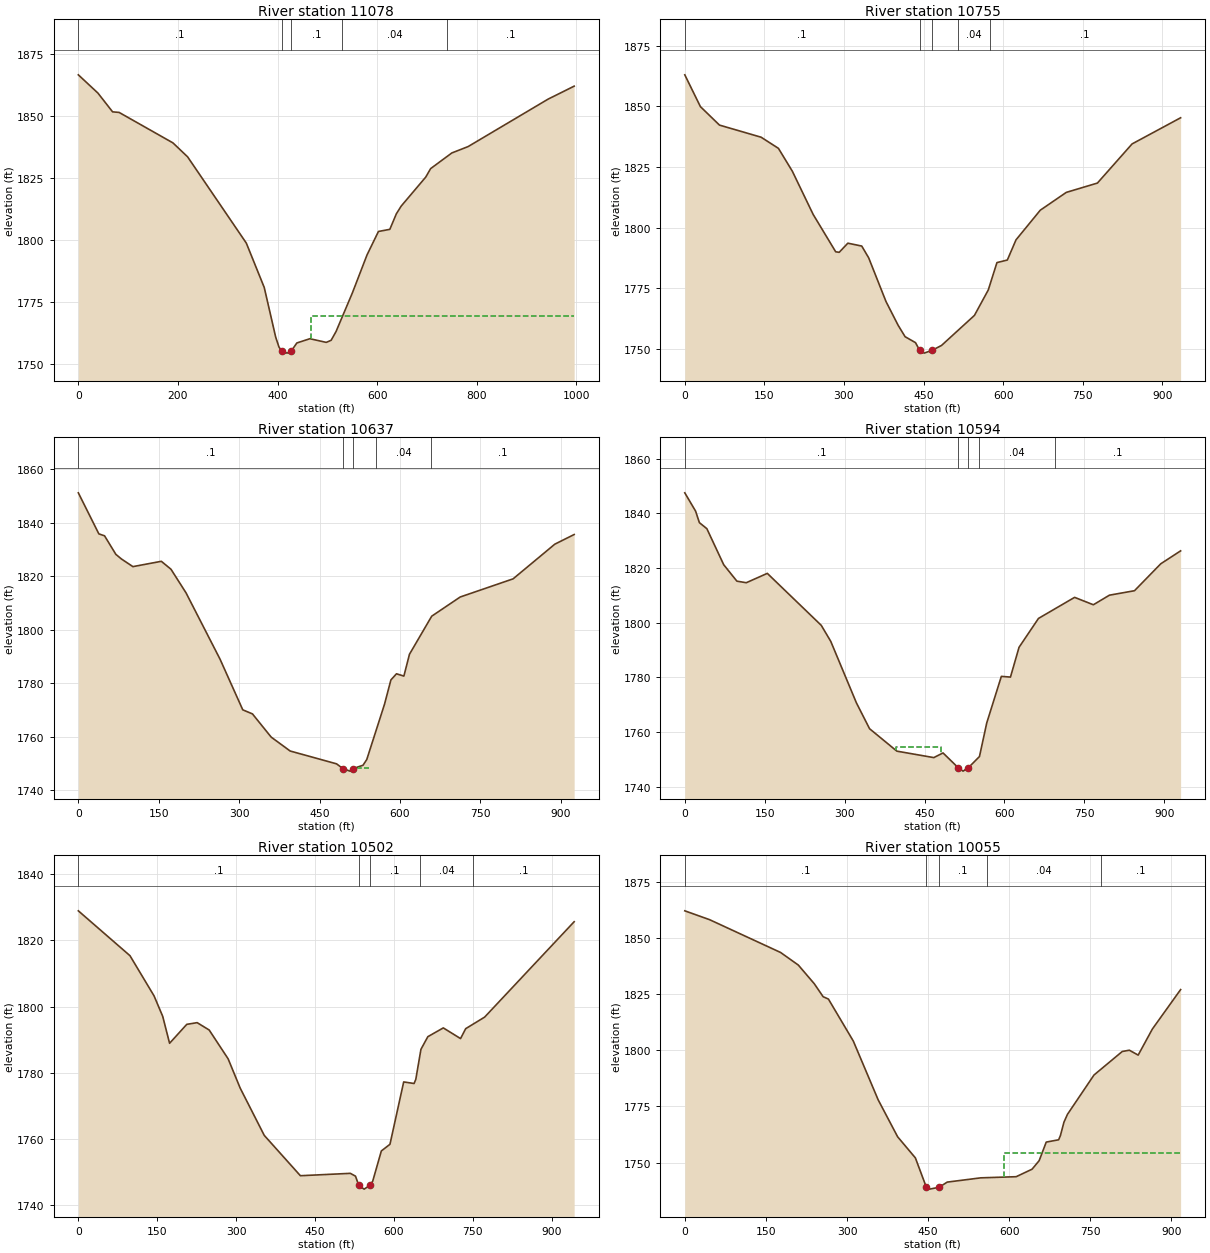
Type RM Length L Ch R = 1 ,11078   ,322.6,322.5,318.2
XS GIS Cut Line= 2
     2074590.218      203914.156     2074788.135       204889.85
#Sta/Elev= 30
       0 1866.58    39.3 1859.23    68.8 1851.65    81.9 1851.42   189.9 1839.15
   219.4 1833.52   337.3 1798.74   373.3 1780.85   396.3 1760.81   402.8 1756.88
  408.091755.242   419.2 1754.37  427.641755.241   438.8 1758.47     465 1760.18
   497.8  1758.7   507.6 1759.54   517.4 1763.04   550.2 1778.61   579.6 1793.92
   602.6 1803.42   625.5 1804.28   638.6 1810.55   648.4 1813.68   697.6 1825.35
   707.4 1828.76     750 1835.08   782.7 1837.65   943.2 1856.77   995.6 1862.01
#Mann= 5 ,-1 , 0
       0      .1       0  408.09    .045       0  427.64      .1       0
     530     .04       0     740      .1       0
#XS Ineff= 2 , 0
                          467.05         1769.36
Permanent Ineff=
       F       F
Bank Sta=408.09,427.64
XS Rating Curve= 0 ,0
Exp/Cntr=0.3,0.1

Type RM Length L Ch R = 1 ,10755   ,117.8,117.7,116.2
XS GIS Cut Line= 3
      2074217.82      203994.311     2074378.046      204419.566
     2074521.694       204877.62
#Sta/Elev= 30
       0 1862.93    29.4 1849.84    65.4 1842.23   143.8 1837.25   176.5 1832.66
   202.7 1823.24   241.9 1805.47   284.4 1790.08     291 1789.86   307.3 1793.62
   333.5 1792.44   346.6 1787.58   379.2 1769.61   402.1 1759.82   415.2 1755.13
   434.8 1752.68  442.451749.579   451.2 1748.36  466.561749.579   483.8 1751.51
   545.9 1763.89     572 1774.37   588.3 1785.63   607.9 1786.68   624.2 1794.98
     670  1807.2     719 1814.53   777.7 1818.37     843 1834.48   934.5 1845.25
#Mann= 5 ,-1 , 0
       0      .1       0  442.45    .045       0  466.56      .1       0
  514.44     .04       0  574.44      .1       0
Bank Sta=442.45,466.56
XS Rating Curve= 0 ,0
Exp/Cntr=0.5,0.3

Type RM Length L Ch R = 1 ,10637   ,42.8,43.5,44.2
XS GIS Cut Line= 4
2074099.32264755204019.386555796 2074267.1492234204441.887026463
2074316.44094498204587.4149663592074416.19800055  204887.8597455
#Sta/Elev= 30
       0 1851.12    38.3 1835.77    48.9 1835.05      70 1828.12    80.6 1826.36
   101.8 1823.53   154.8 1825.52   172.8 1822.56   200.9 1813.72   264.2 1788.98
   306.7    1770   324.8 1768.47   359.7  1759.8   395.1  1754.6   481.7  1749.8
  493.761747.968   506.8 1747.08   511.61747.967     531 1749.28     538 1751.42
   571.1  1772.1     583 1781.17   593.4 1783.47   607.2 1782.61   617.6 1790.75
   659.1    1805   712.3 1812.18   810.9 1818.96   888.7 1831.92   924.8 1835.53
#Mann= 5 ,-1 , 0
       0      .1       0  493.76    .045       0   511.6      .1       0
  554.61     .04       0  658.26      .1       0
#XS Ineff= 2 ,-1
  462.17  488.37 1748.29  518.37  543.05 1748.43
Permanent Ineff=
       F       F
Bank Sta=493.76,511.6
XS Rating Curve= 0 ,0
Exp/Cntr(USF)=0,0
Exp/Cntr=0.5,0.3

Type RM Length L Ch R = 1 ,10594   ,93.1,91.6,90.1
XS GIS Cut Line= 4
2074060.59343774204022.9073930512074231.94085084204463.012049996
2074275.36451033204609.7136023112074368.07989139204900.769482103
#Sta/Elev= 30
       0 1847.53    20.3 1840.82    27.4 1836.61    41.4 1834.41    73.1  1821.2
    97.8  1815.2   115.4 1814.63   154.9 1818.05   256.2 1799.02     274 1793.16
   322.1 1770.67   346.8  1761.2   398.1 1752.98   467.4 1750.62   484.7 1752.33
  513.221746.919   522.3 1745.67   532.21746.916   553.1    1751   566.8 1763.33
   594.2 1780.35   611.3 1780.09   627.4 1790.99   663.9 1801.56   731.7 1809.27
   766.9 1806.56   797.1 1810.07   844.1  1811.7   893.5 1821.57   930.7 1826.29
#Mann= 5 ,-1 , 0
       0      .1       0  513.22    .045       0   532.2      .1       0
  552.28     .04       0  695.28      .1       0
#XS Ineff= 3 ,-1
  396.65  480.791754.614  497.19  509.04 1747.01  536.38  549.75 1747.16
Permanent Ineff=
       F       F       F
Bank Sta=513.22,532.2
XS Rating Curve= 0 ,0
Exp/Cntr(USF)=0,0
Exp/Cntr=0.5,0.3

Type RM Length L Ch R = 1 ,10502   ,445.8,447.2,445.5
XS GIS Cut Line= 2
     2073961.746      204030.475      2074303.76      204908.947
#Sta/Elev= 30
       0 1828.98    98.2 1815.39     144 1803.21   160.4 1797.04   173.5 1788.86
   206.2  1794.6   225.9 1795.11   248.8 1792.88   284.8 1784.16   307.7  1775.3
   353.5 1760.97   422.2 1748.75   517.2 1749.47     527 1748.61  533.151745.819
   543.4 1744.69  554.261745.816   559.7 1747.09   576.1 1756.25   592.5 1758.27
   618.6 1777.16   638.3 1776.68   641.6 1777.92   651.4 1787.03   664.5 1790.86
   693.9 1793.52   726.7 1790.29   736.5 1793.29   772.5 1796.79   942.7 1825.68
#Mann= 5 ,-1 , 0
       0      .1       0  533.15    .045       0  554.26      .1       0
     650     .04       0     750      .1       0
Bank Sta=533.15,554.26
XS Rating Curve= 0 ,0
Exp/Cntr=0.3,0.1

Type RM Length L Ch R = 1 ,10055   ,185.4,187.1,185.4
XS GIS Cut Line= 3
     2073571.257      204126.234     2073776.007      204537.208
     2073901.636      204977.371
#Sta/Elev= 30
       0 1862.21    45.9 1858.26   177.1 1843.65   209.9 1838.04   239.4 1829.72
   255.8 1823.93   265.6 1822.87   311.6 1804.16   357.5    1778   393.6 1761.47
   426.4 1752.07  446.711738.968   452.6 1738.14  470.291738.967   485.3 1741.27
   547.4 1743.17   612.8 1743.68   642.2 1747.03   655.3 1750.83   668.4 1759.11
   691.3 1760.13   694.6 1762.01   701.1 1767.95   707.6 1771.46   756.7 1789.01
     809  1799.5   822.1 1800.07   838.4 1797.89   864.6 1809.49   916.9  1827.1
#Mann= 5 ,-1 , 0
       0      .1       0  446.71    .045       0  470.29      .1       0
  559.15     .04       0  769.15      .1       0
#XS Ineff= 2 , 0
                          590.42         1754.37
Permanent Ineff=
       F       F
Bank Sta=446.71,470.29
XS Rating Curve= 0 ,0
Exp/Cntr=0.3,0.1

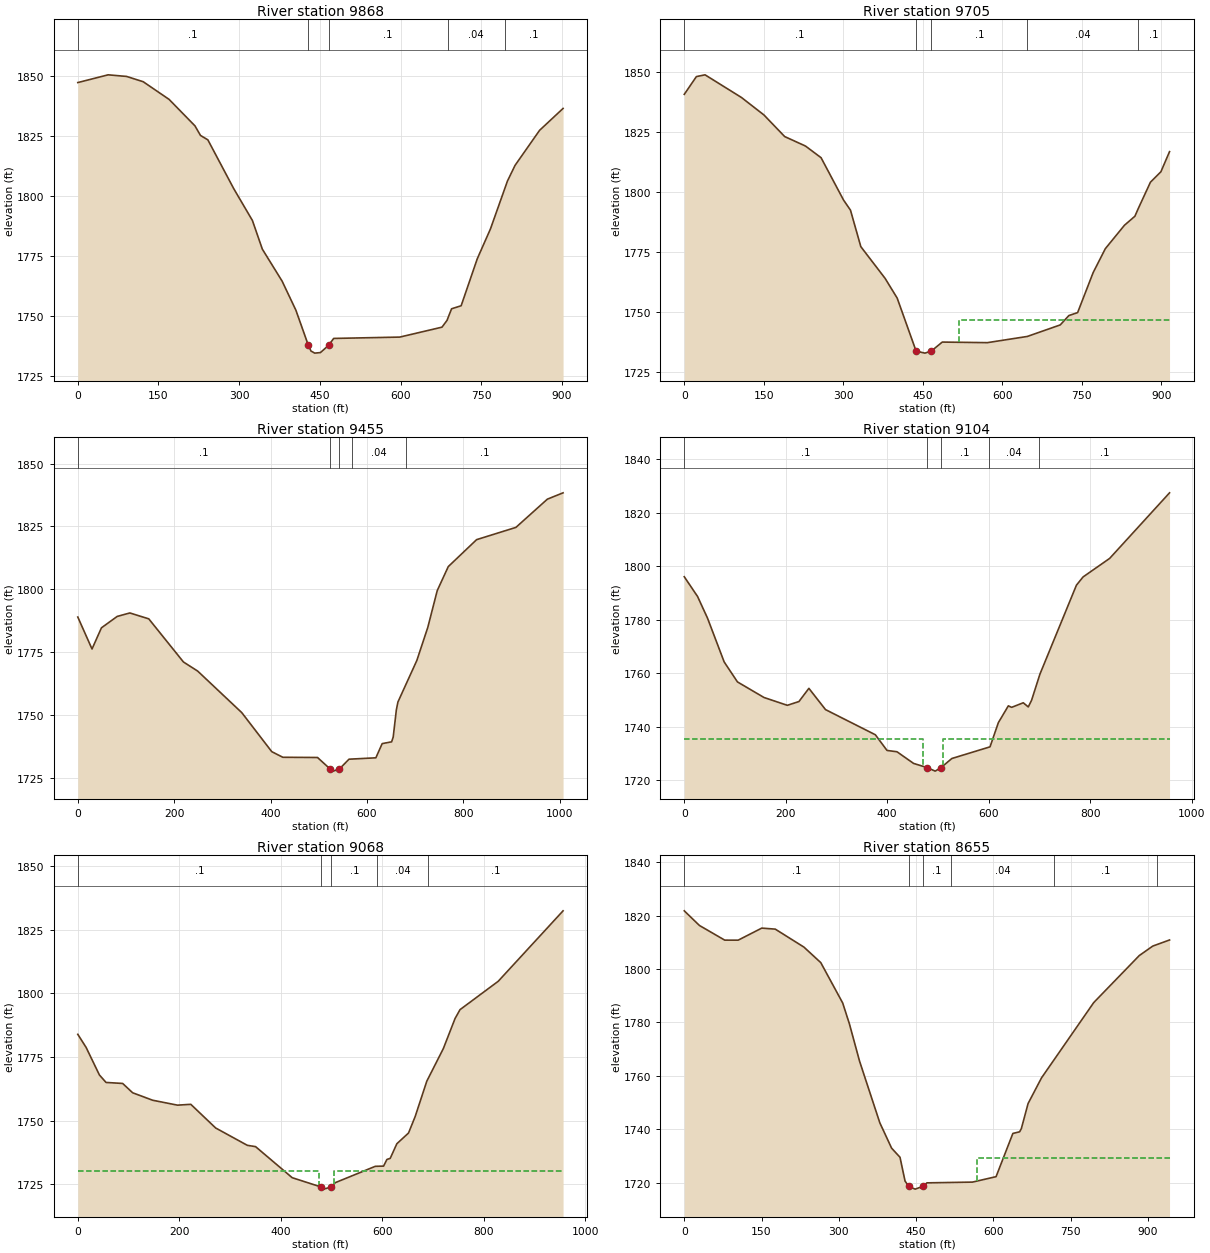
Type RM Length L Ch R = 1 ,9868    ,160.2,162.9,161.4
XS GIS Cut Line= 4
2073460.37492992204178.2690650452073551.36472162204472.469391549
 2073699.9813814204860.6925028122073763.67423559205027.507120933
#Sta/Elev= 30
       0 1847.19    56.4 1850.41    90.7 1849.74   121.6 1847.54   169.7  1840.2
   217.8 1829.19   228.1  1825.2   241.8 1823.37   289.9 1803.07   324.6 1789.85
   343.1 1777.91   379.9 1764.59   405.4 1752.56   428.5    1738   433.5 1735.55
   440.5 1734.67   451.1  1734.9   466.2 1737.91   475.7 1740.78   598.6 1741.34
   677.1 1745.47   686.4 1748.28   694.9 1753.11   712.7 1754.37   742.7 1773.92
   767.2 1786.33   798.8 1806.24   812.9 1812.75   858.5 1827.32   902.2 1836.43
#Mann= 5 ,-1 , 0
       0      .1       0   428.5    .045       0   466.2      .1       0
  687.95     .04       0  793.65      .1       0
Bank Sta=428.5,466.2
XS Rating Curve= 0 ,0
Exp/Cntr(USF)=0,0
Exp/Cntr=0.3,0.1

Type RM Length L Ch R = 1 ,9705    ,255.3,250.6,249.1
XS GIS Cut Line= 3
     2073320.802      204217.871     2073448.863       204653.29
     2073633.172      205076.342
#Sta/Elev= 30
       0 1840.51    22.9 1847.91    39.2 1848.64   107.8 1839.22   150.2 1831.95
   189.4 1822.94   228.6    1819     258 1814.15   300.4 1796.53   313.5 1792.31
     333 1777.12   378.8 1763.92   401.6  1755.7  437.291733.641   453.9  1732.8
  465.921733.643   486.6  1737.4   571.7 1737.16     647 1739.74   709.1 1744.54
   725.5 1748.45   741.9 1749.66   771.3 1766.36   794.2 1776.28   830.2 1786.01
   849.9 1789.77   856.4 1793.02   879.3 1803.96     899 1808.29   915.3 1816.67
#Mann= 5 ,-1 , 0
       0      .1       0  437.29    .045       0  465.92      .1       0
     647     .04       0   856.4      .1       0
#XS Ineff= 2 , 0
       0                     519       0 1746.58
Permanent Ineff=
       F       F
Bank Sta=437.29,465.92
XS Rating Curve= 0 ,0
Exp/Cntr=0.3,0.1

Type RM Length L Ch R = 1 ,9455    ,341.7,350.4,352.6
XS GIS Cut Line= 3
     2073012.093      204316.934     2073298.552      204902.003
     2073296.816      205257.906
#Sta/Elev= 30
       0 1788.94    29.5 1776.22    49.1 1784.65    81.8 1789.18     108 1790.56
   147.3 1788.22   219.3 1771.04   248.8 1767.43   340.4 1750.88   402.6 1735.35
   425.6 1733.11   497.6 1733.03   523.51728.499   530.3  1727.6  543.141728.498
     563 1732.35   618.7  1732.9   631.8 1738.55   651.4 1739.26   654.7 1741.16
   661.2 1751.95   664.5 1755.12   703.7 1771.62   726.5 1784.82   746.1 1799.47
     769 1809.01   827.8 1819.74   909.4 1824.62   974.7 1835.86  1007.3 1838.38
#Mann= 5 ,-1 , 0
       0      .1       0   523.5    .045       0  543.14      .1       0
     570     .04       0  681.43      .1       0
Bank Sta=523.5,543.14
XS Rating Curve= 0 ,0
Exp/Cntr=0.5,0.3

Type RM Length L Ch R = 1 ,9104    ,37.2,36.5,36.2
XS GIS Cut Line= 2
      2072910.27      204330.142     2073015.739      205280.663
#Sta/Elev= 30
       0 1796.06    26.2 1788.67    45.8 1780.58    78.6 1764.19   104.8  1756.7
   157.2 1750.86   203.1 1747.94     226 1749.35   245.6 1754.29   278.4 1746.33
   376.6 1736.92   399.6 1731.05   419.2 1730.56     452 1726.19  478.681724.635
   494.6 1723.31  506.111724.637   527.3 1728.03   602.6  1732.4     619 1741.44
   638.7 1747.74   645.2 1747.18   668.1 1748.89     678 1747.34   684.5 1749.83
   700.9 1759.58   772.9  1792.9     786 1795.98   838.4 1802.92   956.4 1827.46
#Mann= 5 ,-1 , 0
       0      .1       0  478.68    .045       0  506.11      .1       0
     600     .04       0     700      .1       0
#XS Ineff= 2 , 0
          471.35 1735.36  510.03         1735.36
Permanent Ineff=
       F       F
Bank Sta=478.68,506.11
XS Rating Curve= 0 ,0
Exp/Cntr=0.5,0.3

Type RM Length L Ch R = 1 ,9068    ,409.1,412.5,413.4
XS GIS Cut Line= 2
     2072875.114      204339.257     2072980.583      205289.778
#Sta/Elev= 30
       0  1783.9    16.4 1778.75    42.6 1767.94    55.7 1765.01    88.4 1764.62
   108.1 1760.96   147.4 1758.04   196.5  1756.1   222.7 1756.43   271.8 1747.13
   334.1 1740.34   350.4 1739.82   422.5 1727.64  478.731724.042   484.7 1723.15
  499.931724.043   507.6  1725.7   586.3  1732.1   602.6 1732.18   609.2 1734.79
   615.7 1735.22   628.8 1740.96   651.8 1745.17   664.9 1751.63   687.8  1765.5
   720.5 1778.34   743.5 1790.09   753.3 1793.58   828.6 1804.71   956.4 1832.36
#Mann= 5 ,-1 , 0
       0      .1       0  478.73    .045       0  499.93      .1       0
     590     .04       0     690      .1       0
#XS Ineff= 2 , 0
          475.56 1730.23  504.42         1730.34
Permanent Ineff=
       F       F
Bank Sta=478.73,499.93
XS Rating Curve= 0 ,0
Exp/Cntr=0.5,0.3

Type RM Length L Ch R = 1 ,8655    ,340.7,350,351.4
XS GIS Cut Line= 3
     2072579.552      204312.064     2072535.636      204757.951
     2072529.007      205251.499
#Sta/Elev= 30
       0 1821.81    29.4 1816.33    78.5 1810.83   104.6 1810.82   150.4 1815.34
   176.6 1814.95   232.2 1808.22   264.9  1802.4   307.4 1787.29   320.5 1779.42
   340.1 1765.51   379.4 1742.43   402.3 1732.91   418.6 1729.49   428.4 1720.58
   435.71718.546     448 1717.56  462.341718.547   470.9 1719.91   559.2 1720.19
     605 1722.23   637.6 1738.42   650.7 1739.03     654 1740.19   667.1 1749.61
   693.2 1759.24   794.5 1787.44   882.8 1805.04     909  1808.6   941.6 1810.89
#Mann= 6 ,-1 , 0
       0      .1       0   435.7    .045       0  462.34      .1       0
  518.04     .04       0  718.04      .1       0  918.04    .035       0
#XS Ineff= 2 , 0
                          567.34         1729.36
Permanent Ineff=
       F       F
Bank Sta=435.7,462.34
XS Rating Curve= 0 ,0
Exp/Cntr=0.3,0.1