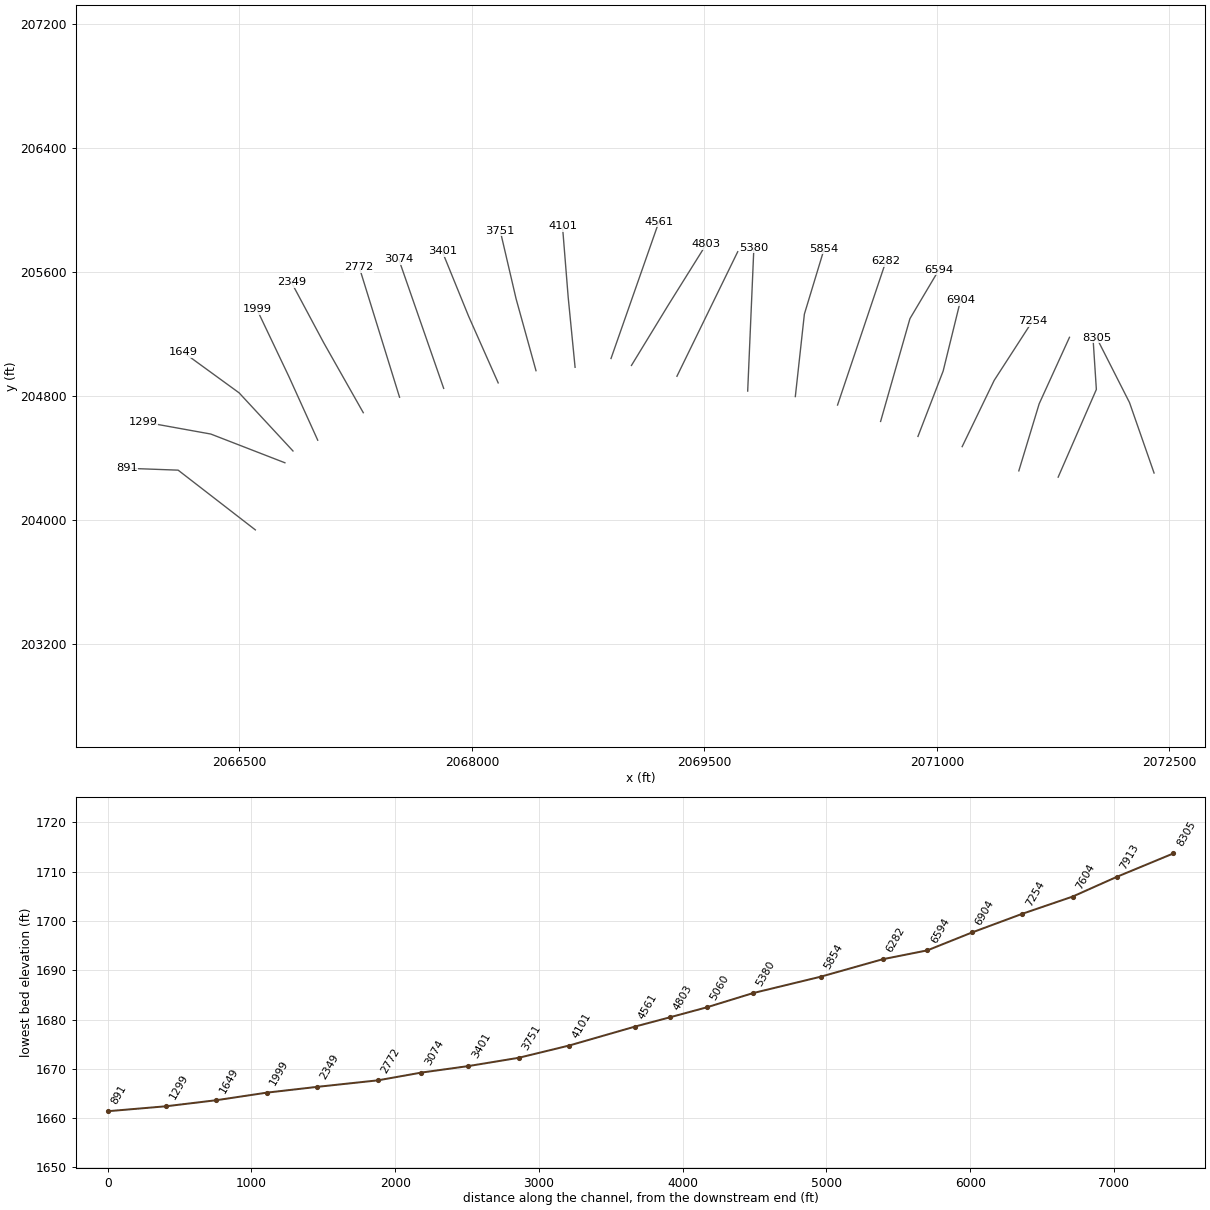
HEC-RAS study LAURELCK1.prj: LAURELCK1

--- LAURELCK1.g01 (geometry) --- (continued)

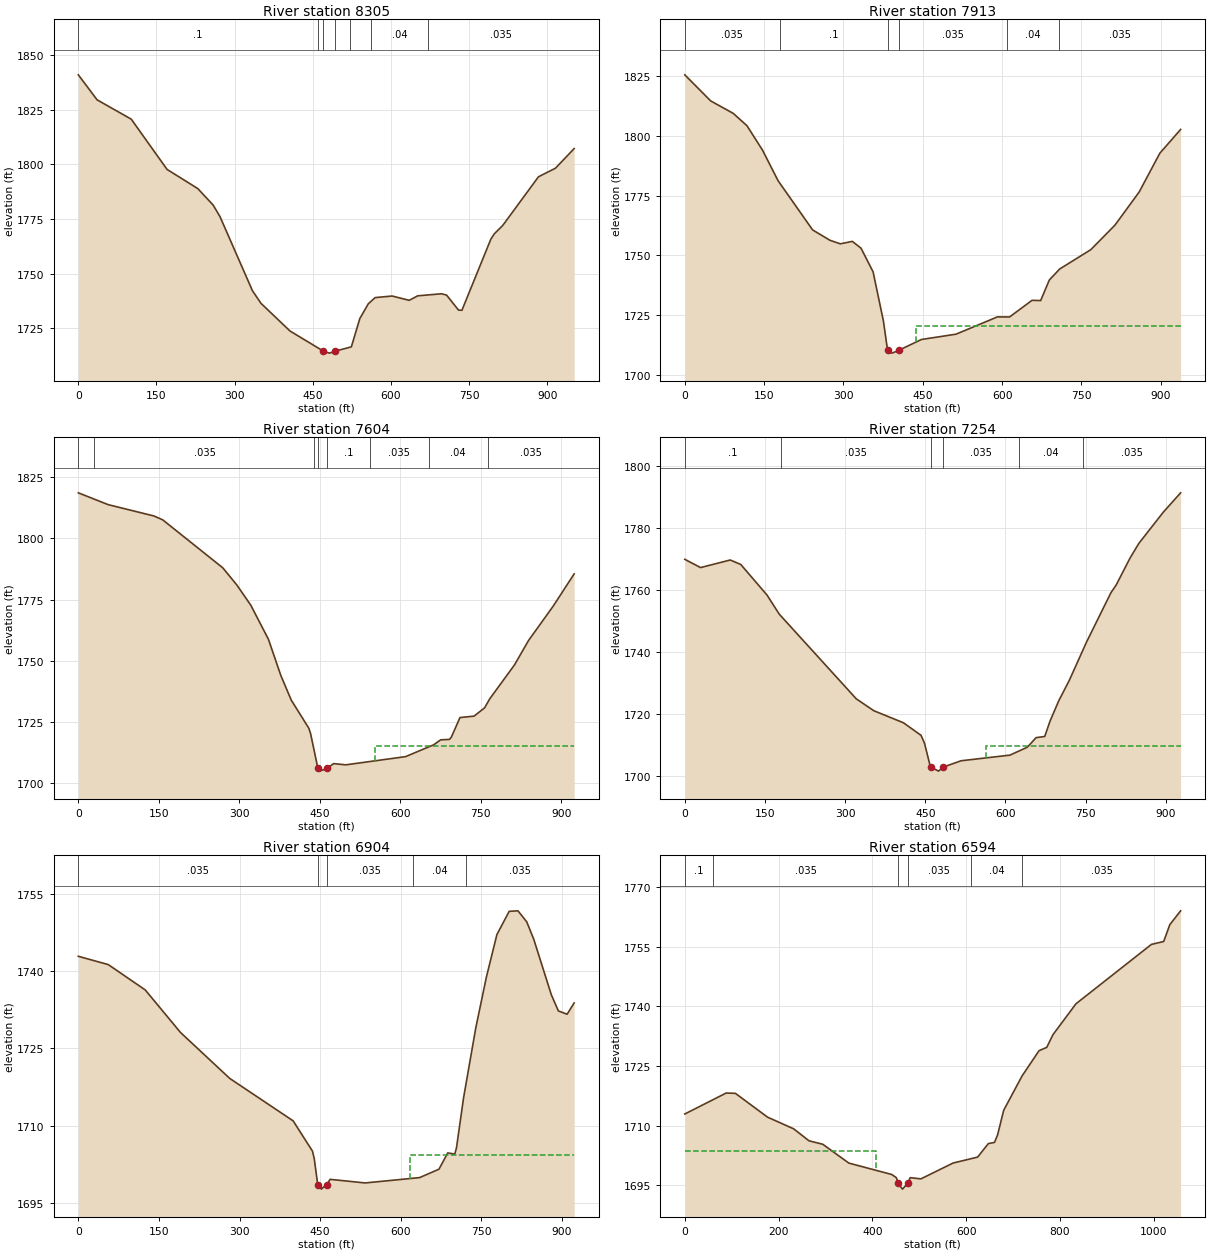
Type RM Length L Ch R = 1 ,8305    ,398.9,392.6,374.6
XS GIS Cut Line= 3
     2072401.781      204301.969     2072243.265      204756.676
     2072030.486      205175.873
#Sta/Elev= 30
       0 1840.89      36 1829.46   101.6 1820.62   170.3 1797.66   229.3  1788.9
   258.8 1781.36   271.9 1776.08   334.1 1742.26   350.5 1736.47   406.2 1723.82
  470.151714.632   481.6  1713.7  493.541714.633     524 1716.56   540.3 1729.52
   556.6 1736.26   569.7 1739.08   602.3  1739.8     635 1737.83   651.3 1739.88
     697 1740.83   706.8 1740.21   729.7 1733.35   736.2 1733.29   791.7 1765.77
   798.2 1768.19   814.5 1772.04   883.1 1794.29   915.7 1798.21   951.6 1807.18
#Mann= 7 ,-1 , 0
       0      .1       0     460    .035       0  470.15    .045       0
  493.54    .035       0  521.55      .1       0  561.55     .04       0
  671.55    .035       0
Bank Sta=470.15,493.54
XS Rating Curve= 0 ,0
Exp/Cntr=0.3,0.1

Type RM Length L Ch R = 1 ,7913    ,306.8,308.9,307
XS GIS Cut Line= 3
     2071782.927      204275.267     2072029.454      204841.239
     2072008.621      205160.684
#Sta/Elev= 30
       0  1825.6      49 1814.66    91.5 1809.46   117.6 1804.26     147 1794.02
   176.4 1781.21   241.7  1760.6   274.4 1756.26     294 1754.77   316.8 1755.79
   333.2 1752.94     356 1743.04   375.6 1722.38   382.2 1712.01  384.651710.111
     392 1708.96  404.24 1710.11   447.5 1714.68   512.8  1716.9   591.2 1724.15
   614.1 1724.11   656.5 1731.08   672.9    1731   689.2 1739.59   708.8 1744.21
   767.6 1752.31   813.3 1762.59   859.1 1776.48   898.3 1792.78   937.5 1802.71
#Mann= 6 ,-1 , 0
       0    .035       0     180      .1       0  384.65    .045       0
  404.24    .035       0     610     .04       0  707.33    .035       0
#XS Ineff= 2 , 0
                          436.96          1720.4
Permanent Ineff=
       F       F
Bank Sta=384.65,404.24
XS Rating Curve= 0 ,0
Exp/Cntr=0.3,0.1

Type RM Length L Ch R = 1 ,7604    ,349.9,350,346
XS GIS Cut Line= 3
     2071529.069      204315.768     2071660.451      204748.874
     2071856.026      205177.606
#Sta/Elev= 30
       0  1818.6    55.8 1813.76     141 1809.14   157.4 1807.54   268.9 1788.02
   295.2 1781.01   321.4 1772.68   354.2 1758.78   377.2 1744.06   396.8 1733.91
   429.6 1722.41   432.9 1720.11  446.391706.051   449.3 1704.94   463.91706.051
   475.5 1708.01   498.4 1707.51   609.7 1710.86     662 1715.68   675.1 1717.72
   691.5  1717.9   694.8 1718.73   711.1 1726.82   737.3  1727.4   756.9 1730.78
   766.8 1734.55   812.6  1748.3   838.7 1758.25   884.6 1772.28   923.8 1785.49
#Mann= 8 ,-1 , 0
       0      .1       0      30    .035       0     440      .1       0
  446.39    .045       0   463.9      .1       0  542.59    .035       0
  652.59     .04       0  762.59    .035       0
#XS Ineff= 2 , 0
                          553.01          1715.1
Permanent Ineff=
       F       F
Bank Sta=446.39,463.9
XS Rating Curve= 0 ,0
Exp/Cntr=0.3,0.1

Type RM Length L Ch R = 1 ,7254    ,345.8,350,353.7
XS GIS Cut Line= 3
      2071163.53      204472.199     2071370.072      204899.758
     2071616.041      205280.192
#Sta/Elev= 30
       0 1769.88    29.5 1767.21    85.1 1769.66   104.8 1768.21   153.9 1758.33
   176.8 1752.16   320.9 1724.81   353.7 1720.97   409.3 1717.06   442.1 1713.01
   448.6 1710.47   458.5 1703.62  460.761702.758   474.8 1701.45  483.81 1702.76
   517.2  1704.8   608.5 1706.62     641 1709.17   657.4 1712.27   673.6 1712.64
   683.4 1717.55   699.7 1724.12   719.3 1730.68   751.9 1743.18   797.5  1759.1
   807.3 1761.58   833.3  1770.3   849.6 1774.99   895.3 1785.07   927.9 1791.36
#Mann= 6 ,-1 , 0
       0      .1       0     180    .035       0  460.76    .045       0
  483.81    .035       0  624.83     .04       0  744.83    .035       0
#XS Ineff= 2 , 0
                          563.04         1709.49
Permanent Ineff=
       F       F
Bank Sta=460.76,483.81
XS Rating Curve= 0 ,0
Exp/Cntr=0.3,0.1

Type RM Length L Ch R = 1 ,6904    ,307.4,310,308.4
XS GIS Cut Line= 3
     2070878.199      204538.135     2071040.826      204960.101
     2071153.116      205417.052
#Sta/Elev= 30
       0 1742.88    55.7 1741.27   124.5 1736.35   190.1 1728.09   281.8 1719.16
   399.8 1710.92   435.8 1705.03   439.1 1703.57  445.541698.538   452.2 1697.66
  462.171698.539   468.6 1699.56   533.9 1698.86   635.2  1699.9   671.2 1701.53
   687.5 1704.69   700.6 1704.47   703.8 1705.67   716.9 1715.35   739.8 1729.02
   759.4 1738.82     779 1747.09   801.9 1751.61   818.2 1751.71   834.5 1749.58
   847.6  1746.2   880.3 1735.41   893.4 1732.27   909.7 1731.63   922.8 1733.82
#Mann= 5 ,-1 , 0
       0    .035       0  445.54    .045       0  462.17    .035       0
  622.22     .04       0  722.22    .035       0
#XS Ineff= 2 , 0
                          617.48         1704.22
Permanent Ineff=
       F       F
Bank Sta=445.54,462.17
XS Rating Curve= 0 ,0
Exp/Cntr=0.3,0.1

Type RM Length L Ch R = 1 ,6594    ,309.9,311.9,310.9
XS GIS Cut Line= 3
     2070637.093      204634.642     2070826.329      205297.836
     2071013.829      205613.809
#Sta/Elev= 30
       0 1712.93    88.2  1718.2   107.9 1718.12   176.5 1712.13   232.1  1709.2
   264.8 1706.19   294.2 1705.32   349.7 1700.59   441.2 1697.72   451.1 1696.92
  454.53 1695.53   464.1 1694.04  475.591695.529   480.5 1696.92   503.4 1696.62
     572  1700.6   624.3 1702.09   647.2 1705.49   660.2 1705.78   666.8 1707.64
   679.9 1713.87   719.2 1722.52   755.3 1728.85   771.7 1729.68   784.8 1732.85
     834 1740.64   994.8 1755.57    1021  1756.3  1034.1 1760.54  1057.1 1764.01
#Mann= 6 ,-1 , 0
       0      .1       0      60    .035       0  454.53    .045       0
  475.59    .035       0     610     .04       0  719.66    .035       0
#XS Ineff= 2 , 0
          407.45  1703.6
Permanent Ineff=
       F       F
Bank Sta=454.53,475.59
XS Rating Curve= 0 ,0
Exp/Cntr=0.3,0.1

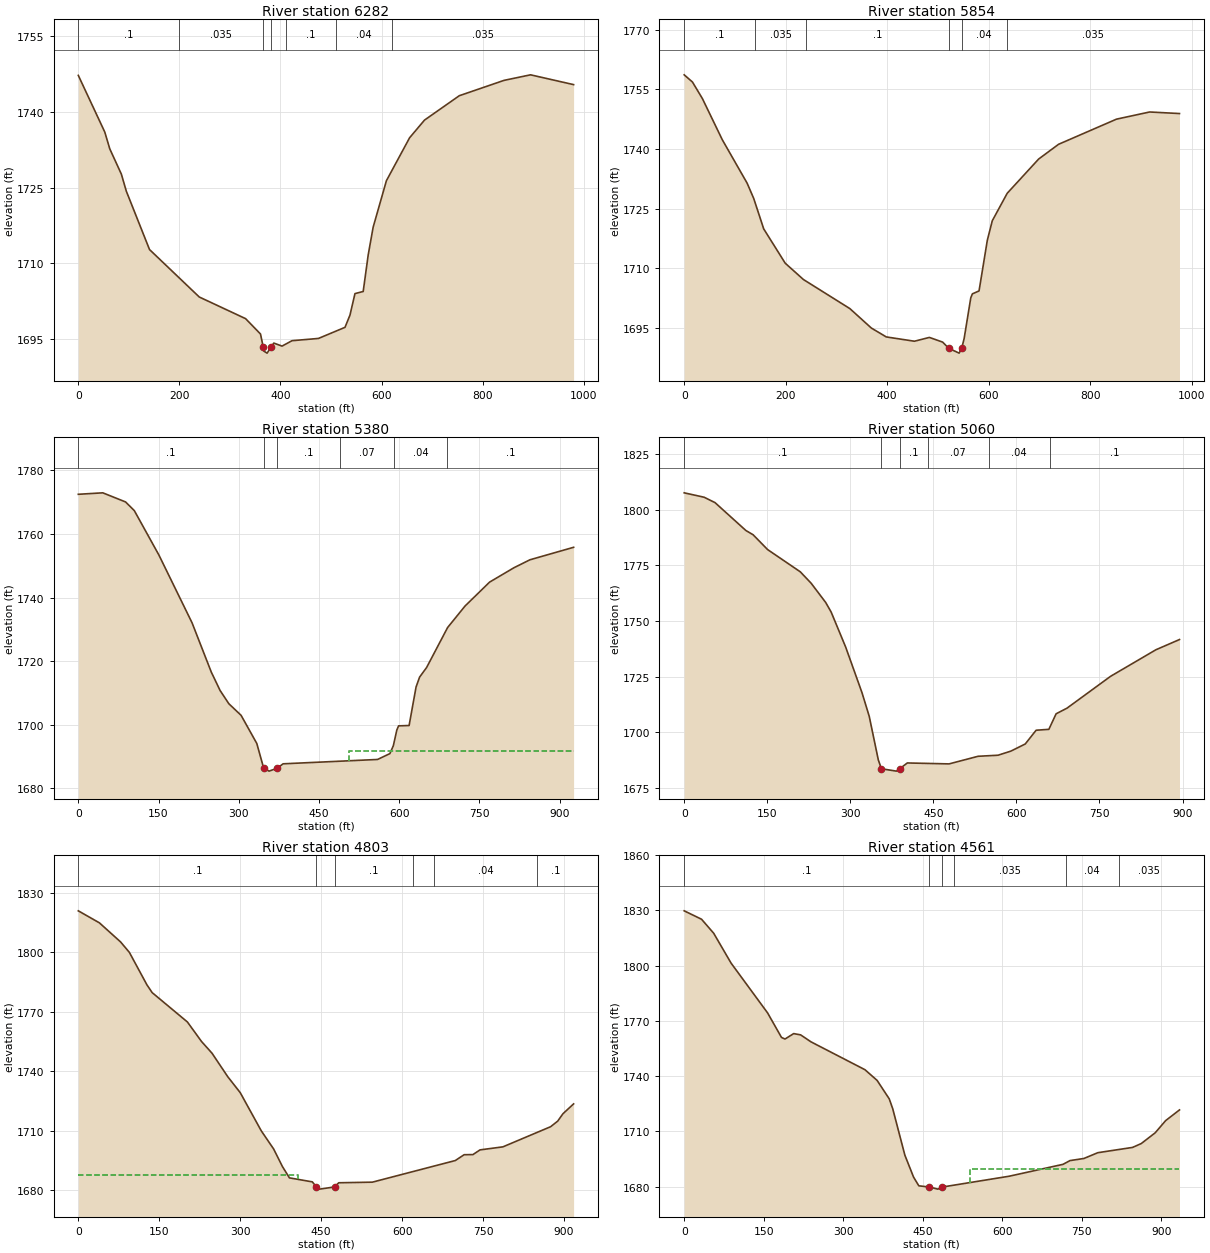
Type RM Length L Ch R = 1 ,6282    ,420,428.1,428.2
XS GIS Cut Line= 2
     2070359.316      204740.545     2070671.816      205669.364
#Sta/Elev= 30
       0 1747.25    52.4 1736.02    62.3 1732.69    85.2 1727.69      95 1724.31
   140.9 1712.75   239.3 1703.35     331 1699.06   360.5 1696.02  365.861693.453
   367.1 1692.63   373.6 1692.23   381.51693.455   386.8 1694.22   403.1 1693.62
   422.8 1694.69   475.2 1695.14   527.7 1697.34   537.5 1699.75   547.4 1704.02
   563.7 1704.44   573.6 1711.69   583.4 1717.18   609.6 1726.38   655.5 1734.89
     685 1738.39   753.8 1743.22   842.3 1746.26   894.8 1747.36     980 1745.42
#Mann= 7 ,-1 , 0
       0      .1       0     200    .035       0  365.86    .045       0
   381.5    .035       0     410      .1       0     510     .04       0
     620    .035       0
Bank Sta=365.86,381.5
XS Rating Curve= 0 ,0
Exp/Cntr=0.3,0.1

Type RM Length L Ch R = 1 ,5854    ,468.8,473.9,474.1
XS GIS Cut Line= 3
     2070086.846      204795.212     2070145.286       205327.41
     2070273.215      205749.136
#Sta/Elev= 30
       0 1758.65    16.3 1756.84    35.9 1752.68    75.1 1742.34   124.1 1731.41
   137.1 1727.56   156.7 1719.94   199.1 1711.31     235 1707.21   326.5  1699.9
   368.9 1695.01   398.3 1692.78   453.8  1691.7   483.2 1692.66   509.3 1691.48
  521.511689.913   541.9 1688.71  546.871689.913   551.7 1692.36   564.8  1702.6
     568 1703.61   581.1 1704.34   597.4 1717.07   607.2 1721.98   636.6 1728.88
   698.6 1737.49   737.8 1741.19     852 1747.51   917.3 1749.31   976.1 1748.92
#Mann= 6 ,-1 , 0
       0      .1       0     140    .035       0     240      .1       0
  521.51    .045       0  546.87     .04       0   635.4    .035       0
Bank Sta=521.51,546.87
XS Rating Curve= 0 ,0
Exp/Cntr=0.3,0.1

Type RM Length L Ch R = 1 ,5380    ,328.5,319.9,312.5
XS GIS Cut Line= 2
     2069779.454      204830.822     2069819.385       205756.17
#Sta/Elev= 30
       0 1772.51    45.8 1772.97    88.4  1770.1   104.7 1767.38   150.6 1753.43
   212.7 1732.06   248.7 1716.53   265.1 1710.76   281.5 1706.58   304.4 1702.93
   333.8 1694.06  346.651686.301   356.7 1685.36  372.34  1686.3   382.9 1687.66
   559.6 1689.03   582.6 1690.87   589.1 1693.35   595.6 1698.28   598.9 1699.61
   618.6 1699.72   631.6 1711.84   638.2 1714.95   651.3 1717.97   690.6 1730.56
   723.3 1737.35   769.1 1744.86   814.9 1749.41   844.4 1751.88   926.2 1755.82
#Mann= 6 ,-1 , 0
       0      .1       0  346.65    .045       0  372.34      .1       0
     490     .07       0     590     .04       0     690      .1       0
#XS Ineff= 2 , 0
                          506.75         1691.77
Permanent Ineff=
       F       F
Bank Sta=346.65,372.34
XS Rating Curve= 0 ,0
Exp/Cntr=0.3,0.1

Type RM Length L Ch R = 1 ,5060    ,258.7,257.2,254.6
XS GIS Cut Line= 2
     2069322.857      204926.309     2069715.218      205730.128
#Sta/Elev= 30
       0 1807.57      36 1805.59    55.7 1803.17   111.4 1790.64   124.5 1788.72
   150.7 1782.06   209.7 1772.07   229.4 1766.91   255.6 1758.28   265.4    1754
   291.6 1738.28   321.1 1717.77   334.2 1707.12   350.6 1687.53  356.171683.552
   383.3 1682.49  389.161683.555     403 1686.16   478.4 1685.74   530.8 1689.16
   566.8 1689.64   589.8 1691.46     616  1694.7   635.6 1700.87   658.6 1701.27
   671.7 1708.26   691.3 1710.78     770 1725.09   851.9 1737.03   894.5 1741.63
#Mann= 6 ,-1 , 0
       0      .1       0  356.17    .045       0  389.16      .1       0
     440     .07       0     550     .04       0     660      .1       0
Bank Sta=356.17,389.16
XS Rating Curve= 0 ,0
Exp/Cntr=0.3,0.1

Type RM Length L Ch R = 1 ,4803    ,237.3,241.3,245.2
XS GIS Cut Line= 3
     2069029.368      204996.126     2069268.821      205388.564
     2069511.464      205776.931
#Sta/Elev= 30
       0 1820.84    39.1 1814.78    78.2 1805.19    94.6  1799.9   127.2 1783.49
   136.9 1779.57   202.2 1764.76   228.2 1754.97   247.8    1749   277.1  1737.1
     300 1729.14   339.1 1709.82   361.9 1700.72   378.2 1691.86   391.2 1686.14
   433.6 1684.12  441.261681.552   446.7 1680.46  474.731681.553   482.6 1683.67
   544.8 1683.97   698.5 1694.88   714.9 1697.82   731.2 1697.88   744.3 1700.25
   786.8 1701.79   875.1 1711.94   888.2 1714.74     898 1718.49   917.7 1723.46
#Mann= 6 ,-1 , 0
       0      .1       0  441.26    .045       0  474.73      .1       0
  619.72    .035       0  659.72     .04       0  849.72      .1       0
#XS Ineff= 2 , 0
          406.17 1687.79
Permanent Ineff=
       F       F
Bank Sta=441.26,474.73
XS Rating Curve= 0 ,0
Exp/Cntr=0.3,0.1

Type RM Length L Ch R = 1 ,4561    ,451.1,460.3,466.2
XS GIS Cut Line= 2
      2068897.51      205040.892     2069206.538      205922.836
#Sta/Elev= 30
       0 1829.78    32.8  1825.2    55.7 1817.59    88.5 1801.37   157.4 1774.31
   183.6    1761   190.2 1760.13   206.6 1763.08   219.7 1762.39   239.4 1758.58
     341 1743.48     364 1737.66   386.9 1727.63   393.5 1722.24   416.4 1697.02
   432.8 1685.12   442.7 1680.39  462.791679.723   478.7 1678.59  486.991679.723
   613.2  1685.6   714.8 1692.06   727.9 1694.09   754.2 1695.24   780.4 1698.38
     846 1701.25   862.4 1703.35   888.6 1709.17   908.3 1715.78   934.5 1721.62
#Mann= 6 ,-1 , 0
       0      .1       0  462.79    .045       0  486.99      .1       0
     510    .035       0     720     .04       0     820    .035       0
#XS Ineff= 2 , 0
                          538.68          1689.4
Permanent Ineff=
       F       F
Bank Sta=462.79,486.99
XS Rating Curve= 0 ,0
Exp/Cntr=0.3,0.1

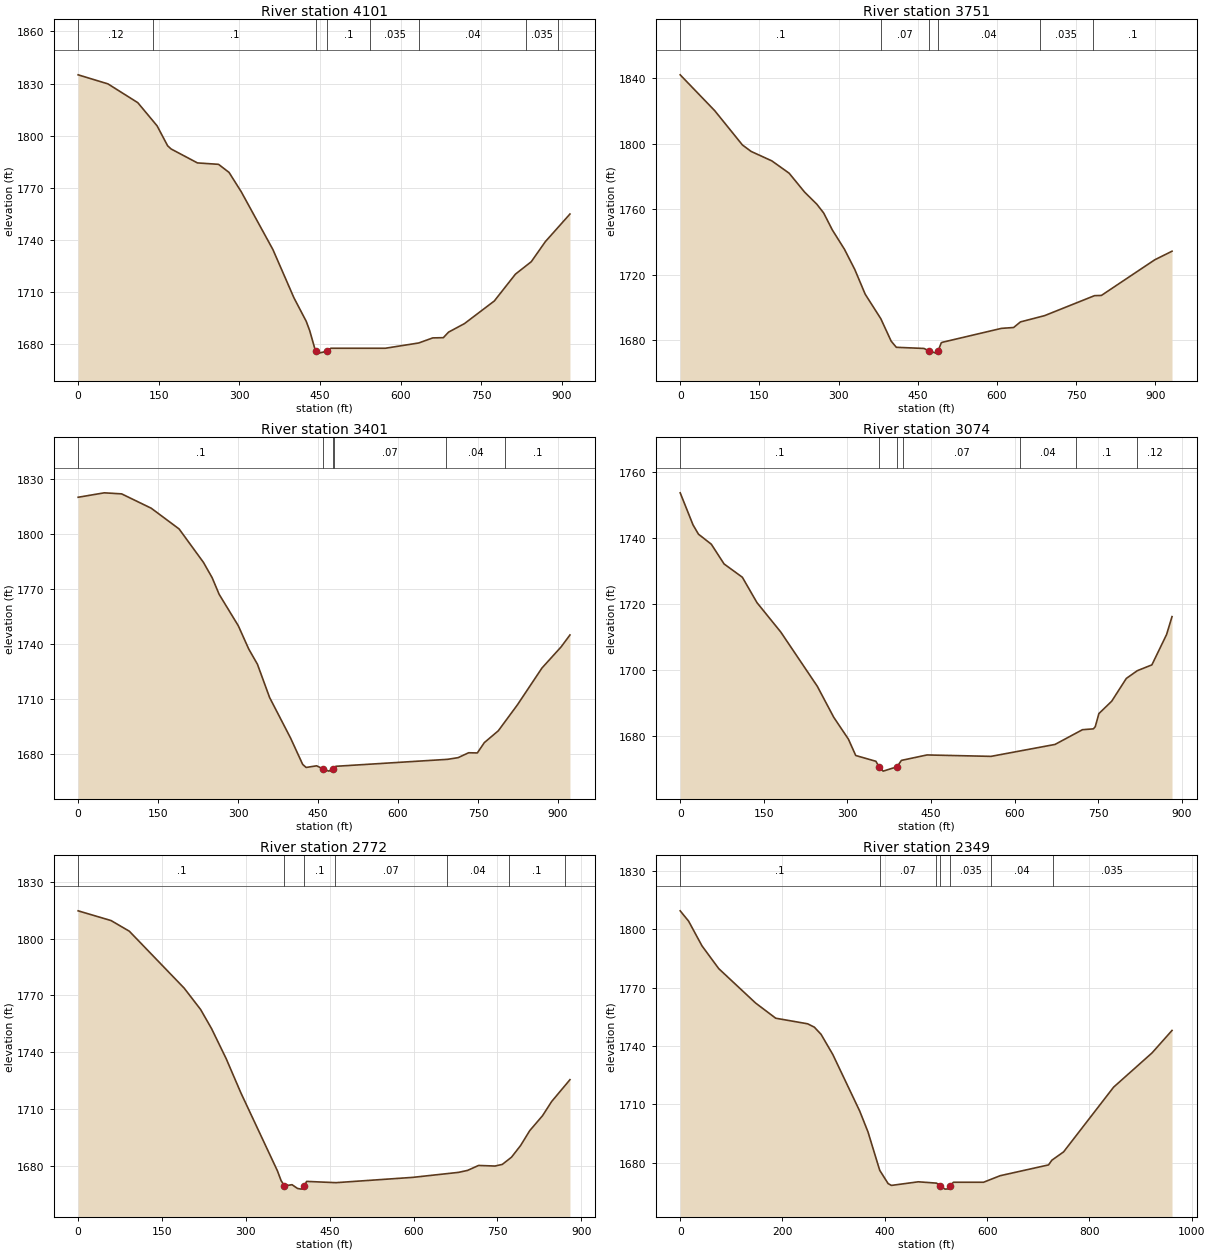
Type RM Length L Ch R = 1 ,4101    ,344.6,350,349.8
XS GIS Cut Line= 3
     2068665.632      204984.139     2068621.153      205435.736
     2068584.196      205895.562
#Sta/Elev= 30
       0 1835.04    55.5 1829.82     111    1819   146.9 1805.67   166.5 1794.18
     173 1792.33     222  1784.3   261.2 1783.48   280.8 1778.83   303.6 1767.63
   362.4  1734.4   401.6 1706.56   424.4 1693.05   430.9 1687.66   440.7    1677
  442.93 1675.79   447.2 1674.73  463.361675.788   470.1 1677.53   571.6 1677.54
   633.7 1680.58   659.9  1683.5   679.5 1683.63   689.3 1686.84   718.8 1691.73
   774.4 1704.78   813.7 1720.24   843.1 1727.38   869.3 1738.94   915.1 1754.86
#Mann= 8 ,-1 , 0
       0     .12       0     140      .1       0  442.93    .045       0
  463.36      .1       0  543.78    .035       0  633.78     .04       0
  833.78    .035       0  893.78      .1       0
Bank Sta=442.93,463.36
XS Rating Curve= 0 ,0
Exp/Cntr=0.3,0.1

Type RM Length L Ch R = 1 ,3751    ,344.1,350,349.8
XS GIS Cut Line= 3
     2068413.403      204962.191     2068284.851      205426.222
     2068182.633       205864.61
#Sta/Elev= 30
       0 1842.18    65.5 1820.26   117.9 1799.35   134.3 1795.42   173.6 1789.64
   206.4 1782.11   235.8 1770.52   258.8 1763.21   271.9 1757.77   288.2 1747.48
   311.2 1735.66   330.8 1723.28   350.5 1708.21     380  1693.3   399.6 1679.61
   409.4 1675.81   461.9  1675.1  470.531673.719   484.8 1672.25  488.741673.716
   494.6 1678.61   497.8 1678.96   608.7 1687.38   631.6 1687.89   644.6 1691.31
   690.3 1695.14   784.9 1707.34   797.9 1707.47     899 1729.24   931.7 1734.48
#Mann= 6 ,-1 , 0
       0      .1       0     380     .07       0  470.53    .045       0
  488.74     .04       0  681.51    .035       0  781.51      .1       0
Bank Sta=470.53,488.74
XS Rating Curve= 0 ,0
Exp/Cntr=0.3,0.1

Type RM Length L Ch R = 1 ,3401    ,323.9,327,321
XS GIS Cut Line= 3
     2068169.403      204883.467     2067978.663      205313.196
     2067808.107      205732.138
#Sta/Elev= 30
       0 1819.88      49  1822.3    81.6 1821.73   137.1 1813.91   189.4  1802.6
   235.1 1784.36   251.4 1776.01   264.5 1766.96   300.4 1749.84     320 1737.15
   336.3 1728.86   359.2 1710.67   398.3  1688.7   421.2 1674.22   427.7 1672.57
   447.3 1673.47   458.41671.935   470.2 1670.57  478.491671.935   483.3  1673.2
     693    1677   712.7 1677.92   732.4 1680.58   748.8 1680.49   761.9 1686.12
   788.1 1692.56   824.2 1706.81     870 1726.79   906.1 1738.37   922.5  1744.8
#Mann= 6 ,-1 , 0
       0      .1       0   458.4    .045       0  478.49      .1       0
  480.16     .07       0  690.16     .04       0  800.16      .1       0
Bank Sta=458.4,478.49
XS Rating Curve= 0 ,0
Exp/Cntr=0.3,0.1

Type RM Length L Ch R = 1 ,3074    ,295.2,302,295.9
XS GIS Cut Line= 2
     2067817.649      204848.184     2067527.718      205681.517
#Sta/Elev= 30
       0 1753.71      23 1743.98    32.8 1741.16    55.8 1738.12    78.7 1732.13
   111.5 1728.09   137.8 1720.37   180.4 1711.47     246 1694.99   275.5 1685.58
   301.8 1678.95   314.9 1673.99     351 1672.24  356.881670.556   364.1 1669.25
  388.881670.557   396.9 1672.51   442.8 1674.16   557.6 1673.73   672.4 1677.35
   721.6 1681.82   741.3 1682.08   744.6 1682.74   751.1 1686.71   774.1 1690.47
   800.3 1697.38     820 1699.73   846.2  1701.5   872.5 1710.69   882.3 1716.14
#Mann= 7 ,-1 , 0
       0      .1       0  356.88    .045       0  388.88      .1       0
     400     .07       0     610     .04       0     710      .1       0
     820     .12       0
Bank Sta=356.88,388.88
XS Rating Curve= 0 ,0
Exp/Cntr=0.3,0.1

Type RM Length L Ch R = 1 ,2772    ,415.6,423.6,423.9
XS GIS Cut Line= 2
     2067532.927      204790.892      2067272.51       205631.17
#Sta/Elev= 30
       0 1814.66    58.9 1809.52    91.6 1803.89   189.7 1773.82   219.1 1762.54
   238.7 1752.43   264.9 1736.52   291.1 1718.52   356.5 1677.32     363 1672.19
  369.111669.381   382.6 1670.02   392.4 1668.04     399 1667.68   402.2 1668.21
  403.961669.383   408.8 1671.76   461.1 1671.09   598.5 1673.89   680.2 1676.52
   696.6 1677.57   716.2 1680.18   745.6 1679.88   758.7 1680.74   775.1 1684.53
   791.4  1690.7   807.8 1698.58   830.6 1706.44     847 1713.97   879.7 1725.48
#Mann= 7 ,-1 , 0
       0      .1       0  369.11    .045       0  403.96      .1       0
     460     .07       0     660     .04       0     770      .1       0
     870     .12       0
Bank Sta=369.11,403.96
XS Rating Curve= 0 ,0
Exp/Cntr=0.3,0.1

Type RM Length L Ch R = 1 ,2349    ,347.1,350,346.1
XS GIS Cut Line= 3
     2067298.837      204691.208     2067043.757      205141.962
     2066834.593       205533.28
#Sta/Elev= 30
       0  1809.6    16.4 1804.31    42.6 1791.57    75.4 1779.84   147.5 1762.12
   186.8 1754.32   249.1 1751.45   262.2 1749.74   275.4 1746.04   298.3 1735.69
   350.8 1706.64   367.1 1695.86   390.1 1676.05   406.5 1669.21     413 1668.26
   465.5 1670.12   501.5 1669.43  507.331668.031   517.9 1666.35   524.4 1666.48
  527.581668.031   534.2 1669.89     593 1669.88   625.6 1673.26   720.2 1678.82
   726.7 1681.24   749.6 1685.52   847.4 1718.84   922.5 1736.46   961.6 1748.03
#Mann= 7 ,-1 , 0
       0      .1       0     390     .07       0     500    .035       0
  507.33    .045       0  527.58    .035       0  607.92     .04       0
  727.92    .035       0
Bank Sta=507.33,527.58
XS Rating Curve= 0 ,0
Exp/Cntr=0.3,0.1

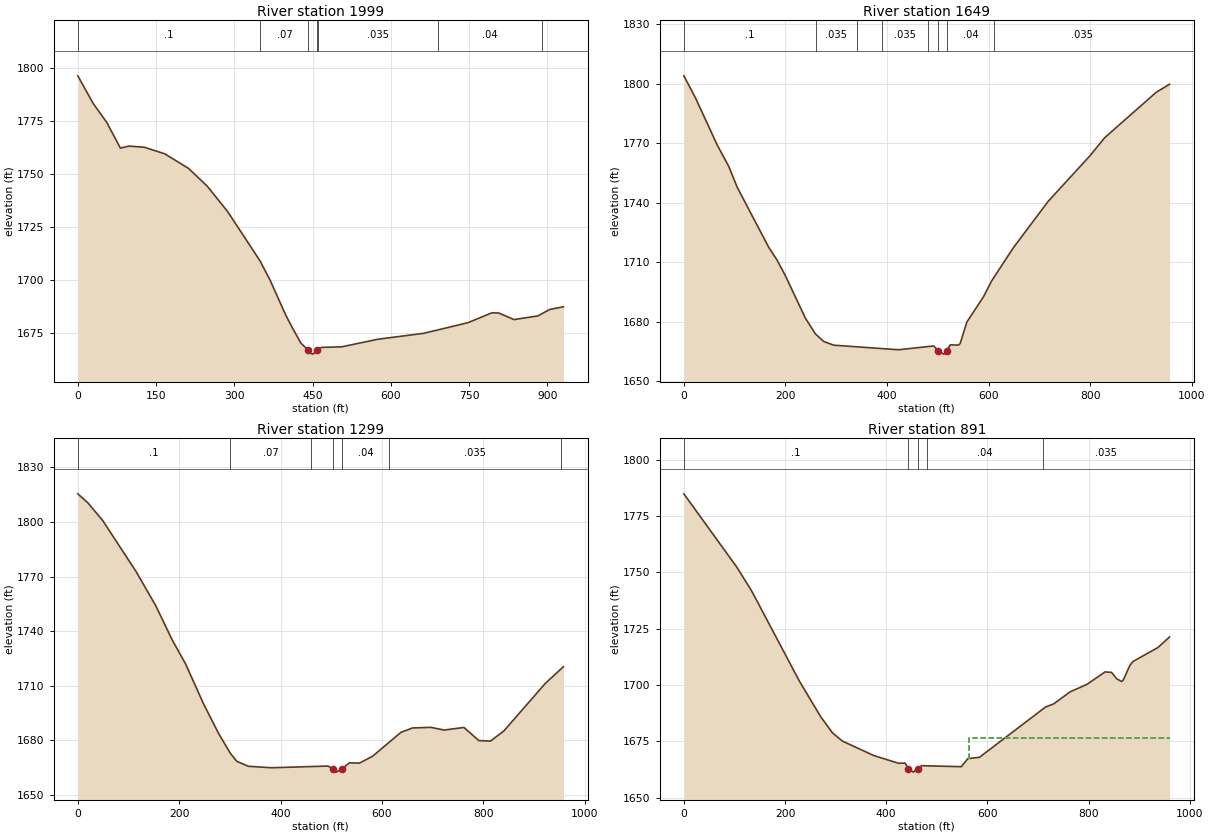
Type RM Length L Ch R = 1 ,1999    ,342.8,350,353.5
XS GIS Cut Line= 3
     2067004.868      204513.761     2066819.014      204923.948
     2066612.548      205357.743
#Sta/Elev= 30
       0 1796.22    29.4 1783.23    55.5 1774.27    81.6 1762.18    97.9 1763.13
   127.3  1762.6   166.4 1759.52   212.1 1752.65     248 1744.28   287.2 1732.28
   349.2 1709.11   368.8 1699.85   398.1 1683.76   411.2 1677.59   427.5  1670.4
  441.671666.954   443.8 1665.78   450.3 1665.18  459.341666.955   466.7 1668.34
   505.9 1668.63   574.5 1672.16   662.8 1674.98   747.7 1679.98   793.5 1684.62
   806.6 1684.56     836 1681.45   881.7 1683.18   904.6 1686.22   930.8 1687.46
#Mann= 7 ,-1 , 0
       0      .1       0     350     .07       0  441.67    .045       0
  459.34     .07       0  460.33    .035       0  690.33     .04       0
  890.33    .035       0
Bank Sta=441.67,459.34
XS Rating Curve= 0 ,0
Exp/Cntr=0.3,0.1

Type RM Length L Ch R = 1 ,1649    ,338.7,350,353.3
XS GIS Cut Line= 3
     2066845.171      204444.163      2066497.53      204819.277
      2066137.66      205080.979
#Sta/Elev= 30
       0 1803.98      23  1792.8    65.6 1769.14    88.5 1758.28   104.9 1747.87
   167.2 1717.48   183.6 1711.06     200 1703.17   239.3  1681.8     259 1673.87
   275.4 1670.04   295.1 1668.16   422.9 1665.86   491.8 1667.77  501.34 1665.41
   511.4 1663.65   514.7  1663.9  517.771665.407   524.5 1668.33   540.9 1668.19
   544.2 1669.07   557.2 1679.77     590 1692.57   606.3 1700.65   648.8 1717.29
   717.6 1740.74   799.4 1763.58   828.8  1772.8   930.2 1795.68   956.4 1799.73
#Mann= 8 ,-1 , 0
       0      .1       0     260    .035       0     340     .07       0
     390    .035       0     480     .04       0  501.34    .045       0
  517.77     .04       0  611.43    .035       0
Bank Sta=501.34,517.77
XS Rating Curve= 0 ,0
Exp/Cntr=0.3,0.1

Type RM Length L Ch R = 1 ,1299    ,405.9,407.1,395.7
XS GIS Cut Line= 3
     2066793.074      204368.046     2066314.775      204553.461
      2065876.84      204632.481
#Sta/Elev= 30
       0 1815.49    19.6 1810.61      49 1800.84   114.4 1772.98   153.6 1754.03
   186.2 1735.13   212.4 1722.04   248.3  1699.8   277.7  1683.7   300.6 1672.87
   313.7 1668.35   336.5 1665.64   382.3 1664.83   493.4 1665.77  502.621664.312
   509.7 1662.42  521.491664.311   535.9 1667.56   555.5 1667.37   581.7 1671.21
   637.3 1684.29   660.2 1686.71   696.2 1687.06   722.4 1685.57   761.7 1686.99
   791.1 1679.76     814 1679.51   840.2 1685.01     922 1711.18     958 1720.43
#Mann= 7 ,-1 , 0
       0      .1       0     300     .07       0     460     .04       0
  502.62    .045       0  521.49     .04       0  612.98    .035       0
  952.98      .1       0
Bank Sta=502.62,521.49
XS Rating Curve= 0 ,0
Exp/Cntr=0.3,0.1

Type RM Length L Ch R = 1 ,891     ,446.1,446.8,438.4
XS GIS Cut Line= 3
     2066602.371      203934.989     2066104.107      204320.406
     2065774.246      204332.559
#Sta/Elev= 30
       0 1784.79   104.4 1752.37   133.8 1741.82   228.5  1701.7   270.9 1685.82
   293.8 1678.81   313.3 1675.18   375.4 1668.77   424.3 1665.34   437.4 1665.39
  443.681662.979   453.7 1661.41  462.37 1662.98     470 1664.27   548.3 1663.82
   561.4 1667.41   584.2 1667.97   714.9 1690.26   731.2  1691.7   763.9 1697.06
   796.6 1700.29   832.6 1705.84   845.6 1705.61   855.4 1702.82   865.2 1701.59
   868.5 1702.21   881.6 1708.71   888.1  1710.5   937.1 1716.65     960 1721.34
#Mann= 5 ,-1 , 0
       0      .1       0  443.68    .045       0  462.37      .1       0
     480     .04       0  709.93    .035       0
#XS Ineff= 2 , 0
                          563.04         1676.69
Permanent Ineff=
       F       F
Bank Sta=443.68,462.37
XS Rating Curve= 0 ,0
Exp/Cntr=0.3,0.1