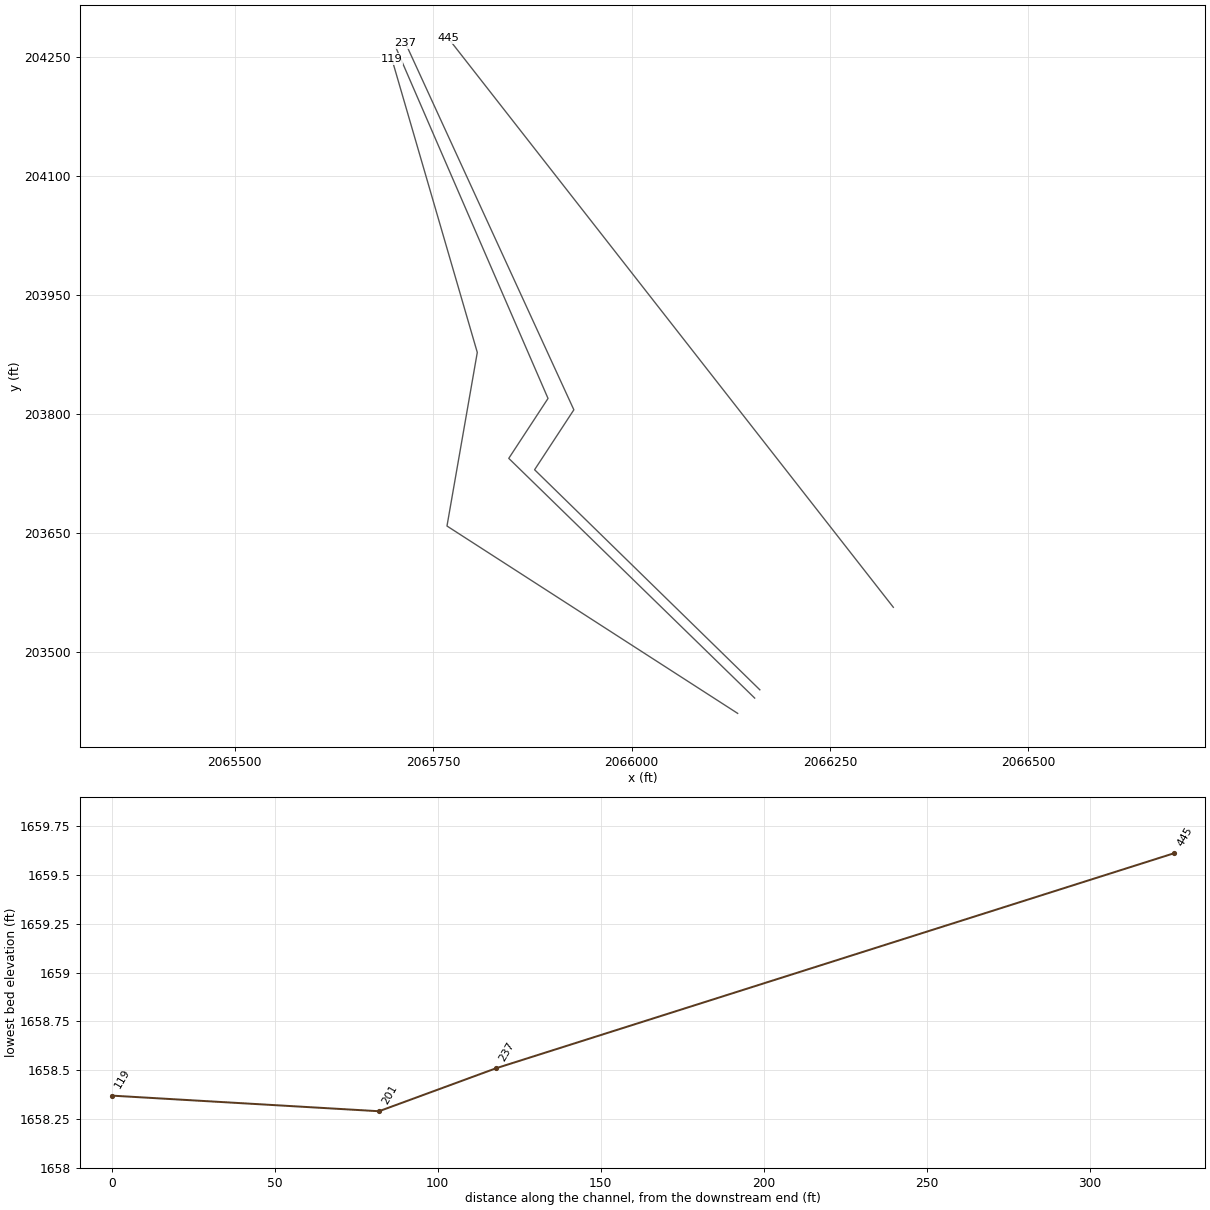
HEC-RAS study LAURELCK1.prj: LAURELCK1

--- LAURELCK1.g01 (geometry) --- (continued)

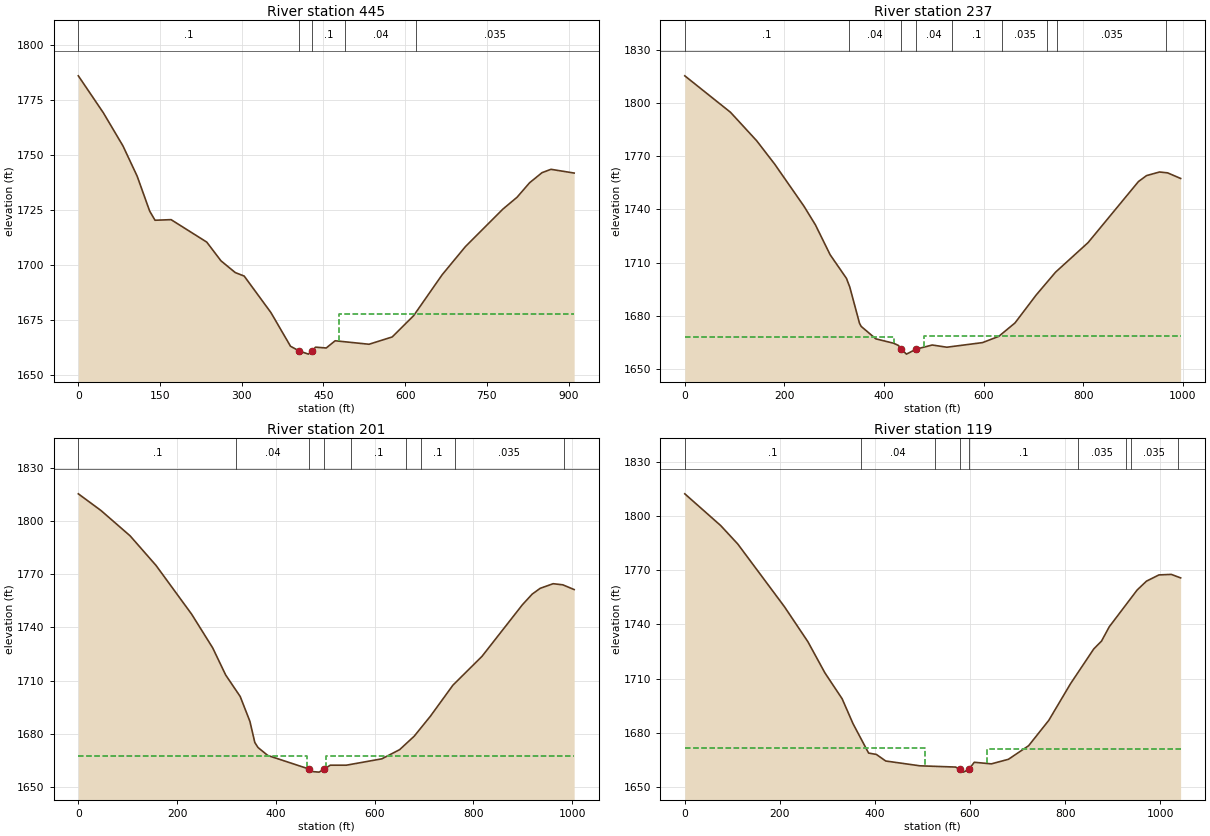
Type RM Length L Ch R = 1 ,445     ,227,207.8,177.7
XS GIS Cut Line= 2
     2066329.802      203556.517     2065769.038      204273.531
#Sta/Elev= 30
       0 1785.89    45.8 1769.17    81.9 1754.11     108 1740.37     131  1724.5
   140.8 1720.36   170.3 1720.63   235.8 1710.44   261.9 1701.94   288.1 1696.62
   304.5 1695.03   353.6 1678.46   389.6 1663.17  405.751661.025   422.4 1659.61
  428.911661.024   435.5 1662.77   455.1  1662.4   471.5 1665.67   533.7 1664.09
   576.3 1667.41   615.6 1677.07     668 1695.64   710.5 1708.36   779.3 1725.38
   805.5  1730.8   828.4 1737.35   851.3 1741.95   867.7 1743.47   910.3 1741.77
#Mann= 5 ,-1 , 0
       0      .1       0  405.75    .045       0  428.91      .1       0
     490     .04       0     620    .035       0
#XS Ineff= 2 , 0
                          478.51         1677.79
Permanent Ineff=
       F       F
Bank Sta=405.75,428.91
XS Rating Curve= 0 ,0
Exp/Cntr=0.5,0.3

Type RM Length L Ch R = 1 ,237     ,36.3,35.9,38.7
XS GIS Cut Line= 4
     2066161.572      203452.538     2065877.718      203729.882
     2065927.197      203805.403     2065714.958      204267.642
#Sta/Elev= 30
       0 1815.18    91.8 1794.65   144.3 1778.65   180.4 1765.52   239.4 1741.76
   262.4 1731.25   291.9 1714.47   324.7 1701.14   331.3 1696.33   350.9 1675.87
   354.2 1674.13   383.7 1667.11   419.4 1664.64   429.1 1663.38  434.55 1661.36
   445.2 1658.51   464.6 1661.31   496.9 1663.64   526.3  1662.4     598    1665
   630.6 1668.51   663.2 1676.08   705.6 1691.76   744.7 1704.67   809.9 1721.28
     911 1755.63   927.3 1759.01   953.4 1761.04   969.7 1760.55   995.8 1757.41
#Mann= 9 ,-1 , 0
       0      .1       0     330     .04       0  434.55    .045       0
   464.6     .04       0  537.14      .1       0  637.14    .035       0
  727.14      .1       0  747.14    .035       0  967.14      .1       0
#XS Ineff= 2 , 0
          419.22 1668.06  480.57         1668.46
Permanent Ineff=
       F       F
Bank Sta=434.55,464.6
XS Rating Curve= 0 ,0
Exp/Cntr=0.5,0.3

Type RM Length L Ch R = 1 ,201     ,75,82,90.5
XS GIS Cut Line= 4
     2066155.062      203442.122     2065845.166      203744.205
     2065894.645      203819.726     2065703.239      204261.132
#Sta/Elev= 30
       0 1815.42    45.9 1805.99   104.9 1791.69   157.4 1774.98   229.5 1747.46
   272.1 1728.46   298.4 1713.15   327.9 1700.96   347.5 1686.95   357.4 1675.05
   363.9 1672.19   383.6 1667.71  466.771660.079   474.7 1658.58   487.6 1658.29
   498.51660.078   510.2 1662.21   542.7  1662.2   614.7  1665.8   650.7 1670.97
   680.2 1678.56   712.9 1689.81   758.7 1707.39   817.6 1723.68   899.4  1752.8
   919.1 1758.77   935.4 1762.07   961.6 1764.67   981.3 1764.04  1004.2 1761.36
#Mann= 9 ,-1 , 0
       0      .1       0     320     .04       0  466.77    .045       0
   498.5     .04       0  553.06      .1       0  663.06    .035       0
  693.06      .1       0  763.06    .035       0  983.06      .1       0
#XS Ineff= 2 , 0
          462.71 1667.45   501.8         1667.29
Permanent Ineff=
       F       F
Bank Sta=466.77,498.5
XS Rating Curve= 0 ,0
Exp/Cntr=0.5,0.3

Type RM Length L Ch R = 1 ,119     ,118.3,119,118.9
XS GIS Cut Line= 4
     2066133.621      203422.836     2065767.302      203658.947
     2065805.496      203877.697     2065697.857      204247.489
#Sta/Elev= 30
       0 1812.25    75.4 1794.73   111.4 1784.52   209.7  1749.8   258.9  1730.5
   294.9 1713.19     331 1698.92   353.9 1685.14   386.7  1668.9     403 1668.15
   422.7 1664.52   494.6 1661.86   569.7 1661.17  578.491659.843     586 1658.37
  597.481659.841   608.9 1663.82   644.8 1662.94   680.7 1665.46   723.2 1672.96
   765.6 1686.97   811.3 1707.22   860.2 1726.46   876.6 1730.83   892.9 1738.74
   951.6 1759.09   971.2 1763.98   997.3 1767.41  1023.4  1767.7    1043 1765.77
#Mann= 9 ,-1 , 0
       0      .1       0     370     .04       0  525.82      .1       0
  578.49    .045       0  597.48      .1       0  827.88    .035       0
  927.88      .1       0  937.88    .035       0 1037.88      .1       0
#XS Ineff= 2 , 0
          505.44 1671.79   636.1         1670.99
Permanent Ineff=
       F       F
Bank Sta=578.49,597.48
XS Rating Curve= 0 ,0
Exp/Cntr=0.3,0.1
LCMann Table=0

Chan Stop Cuts=-1
Use User Specified Reach Order=0
Composite Channel Slope=5